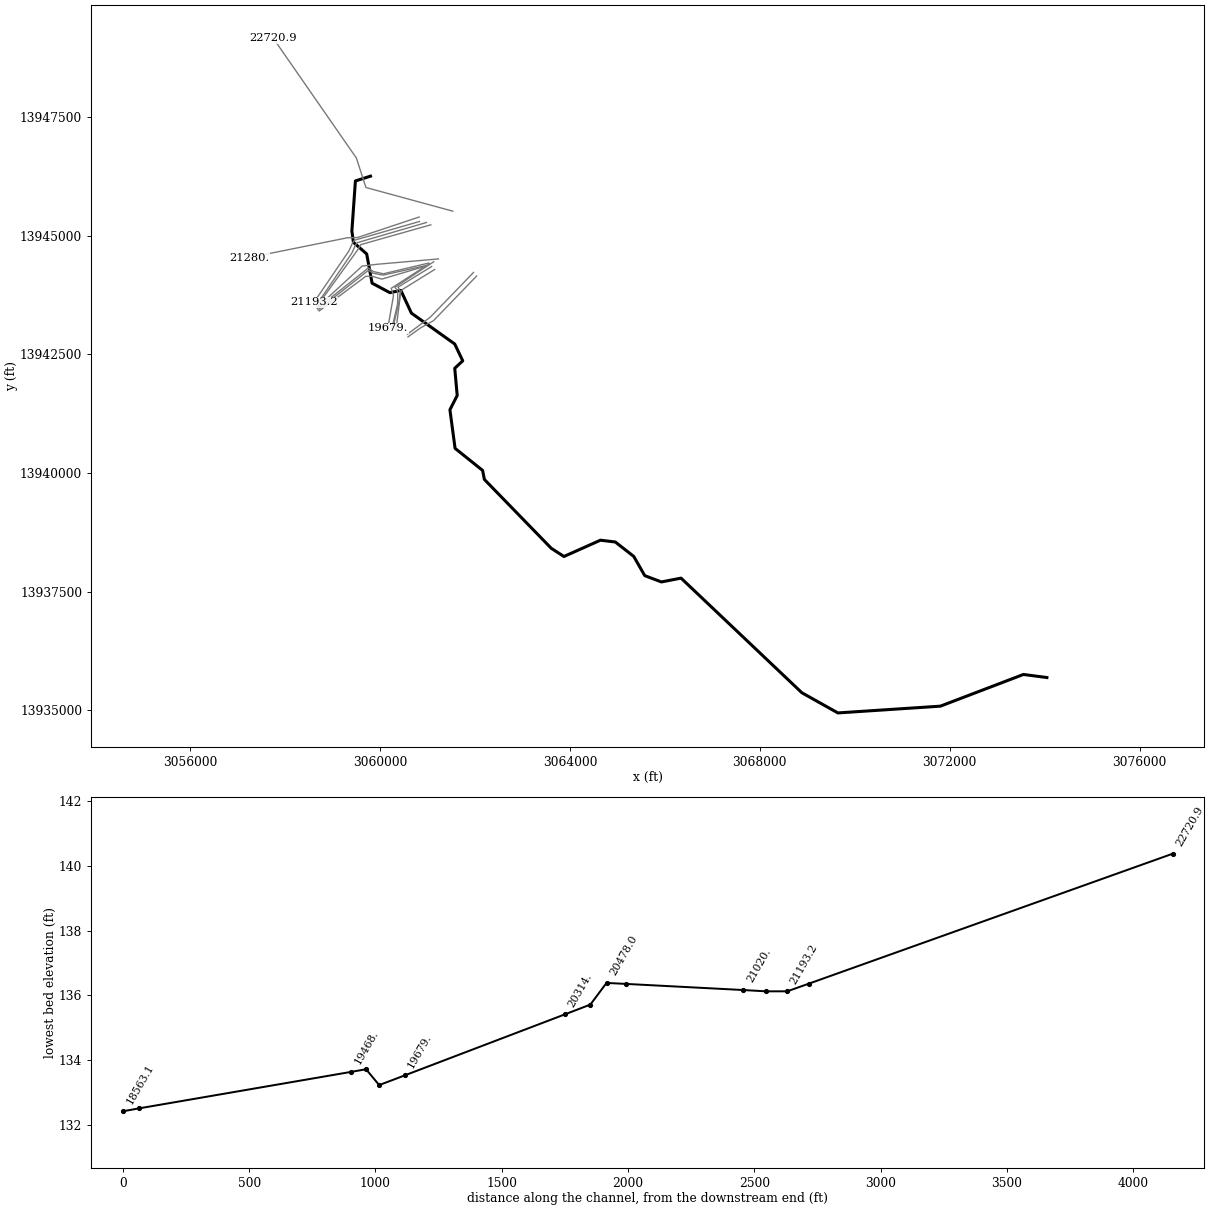
--- K131-02-00.prj (project) ---

Proj Title=K131-02-00
Current Plan=p02
Default Exp/Contr=.3,.1
English Units
Geom File=g01
Flow File=f02
Flow File=f01
Flow File=f04
Plan File=p01
Plan File=p04
Plan File=p02
Y Axis Title=Elevation
X Axis Title(PF)=Main Channel Distance
X Axis Title(XS)=Station
BEGIN DESCRIPTION:
Cypress Creek Watershed
Theiss Gully
HCFCD Unit K131-02-00 and K131-02-04
Flood Hazard Model
10, 2, 1, 0.2%
Filename K131-02-00
Prepared by:  Halff Associates Inc  DATE:  February 23, 2004
Reviewed by:  _________  DATE:  __________________
STATUS (Final)
Confluence of K131-02-00 and K131-02-04 approximately 800' downstream of Spring-Cypress Road.
END DESCRIPTION:
DSS File=dss
DSS Export Rating Curves= 0
DSS Export Rating Curve Sorted= 0
DSS Export Volume Flow Curves= 0
DXF OffsetX= 0
DXF OffsetY= 0
DXF ScaleX= 1
DXF ScaleY= 10

--- K131-02-00.p02 (plan) ---

Plan Title=Floodway
Version=Version 3.0.1  Mar 2001
Short Identifier=Floodway0607
Geom File=g01
Flow File=f02
Subcritical Flow
K Sum by GR= 0
Std Step Tol= 0.01
Critical Tol= 0.01
Num of Std Step Trials= 20
Max Error Tol= 0.3
Flow Tol Ratio= 0.001
Split Flow NTrial= 30
Split Flow Tol= 0.02
Split Flow Ratio= 0.02
Log Output Level= 0
Friction Slope Method= 1
Unsteady Friction Slope Method= 2
Parabolic Critical Depth
Global Vel Dist= 0 , 0 , 0
Global Log Level= 0
CheckData=True
Encroach Param=-1 ,0,0, 3
Encroach River=K131-02-00
Encroach Reach=Reach - 1
Encroach Node=22720.9
       1 4129.58 5109.09       1 4129.58 5109.09
Encroach Node=21280.
       1 4524.01 5094.29       1 4524.01 5094.29
Encroach Node=21193.2
       1 4524.01 5094.29       1 4524.01 5094.29
Encroach Node=21151.4
       1 4524.01 5094.29       1 4524.01 5094.29
Encroach Node=21109.5
       1 4524.01 5094.29       1 4524.01 5094.29
Encroach Node=21020.
       1 4524.01 5094.29       1 4524.01 5094.29
Encroach Node=20554.
       1    4500    5068       1    4500    5068
Encroach Node=20478.0
       1 3613.04 4018.09       1 3613.04 4018.09
Encroach Node=20446.0
       1 3613.04 4018.09       1 3613.04 4018.09
Encroach Node=20414.0
       1 3613.04 4018.09       1 3613.04 4018.09
Encroach Node=20314.
       1 4524.01  5031.2       1 4524.01  5031.2
Encroach Node=19679.
       1 4881.29 5201.52       1 4881.29 5201.52
Encroach Node=19577.8
       1 4881.29 5201.52       1 4881.29 5201.52
Encroach Node=19551.8
       1 4881.29 5201.52       1 4881.29 5201.52
Encroach Node=19525.8
       1 4881.29 5201.52       1 4881.29 5201.52
Encroach Node=19468.
       1 4881.29 5201.52       1 4881.29 5201.52
Encroach Node=18627.
       1 4726.78  5041.5       1 4726.78  5041.5
Encroach Node=18563.1
       1 4726.78  5041.5       1 4726.78  5041.5
Encroach Node=18533.1
       1 4726.78  5041.5       1 4726.78  5041.5
Encroach Node=18503.1
       1 4726.78  5041.5       1 4726.78  5041.5
Encroach Node=18417.
       1 4656.01  5010.7       1 4656.01  5010.7
Encroach Node=17991.
       1 4755.53    5120       1 4755.53    5120
Encroach Node=17886.3
       1  4737.9    5100       1  4737.9    5100
Encroach Node=17838.8
       1  4737.9 5038.69       1  4737.9 5038.69
Encroach Node=17791.3
       1  4737.9    5100       1  4737.9    5100
Encroach Node=17688.
       1    4760    5120       1    4760    5120
Encroach Node=16029.9
       1  4774.7    5200       1  4774.7    5200
Encroach Node=15545.3
       1 4913.46 5063.64       1 4913.46 5063.64
Encroach Node=13933.0
       1    4950  5042.9       1    4950  5042.9
Encroach Node=12305.1
       1  4948.1  5048.3       1  4948.1  5048.3
Encroach Node=11553.3
       1    4920  5041.2       1    4920  5041.2
Encroach Node=10364.8
       1    4969  5050.1       1    4969  5050.1
Encroach Node=10285.5
       1    4900    5100       1    4900    5100
Encroach Node=10257.5
       1    4900    5100       1    4900    5100
Encroach Node=10229.5
       1    4900    5100       1    4900    5100
Encroach Node=10157.0
       1  4959.9 5080.04       1  4959.9 5080.04
Encroach Node=10146.5
       1  4959.9 5080.04       1  4959.9 5080.04
Encroach Node=10136.0
       1  4956.3 5080.04       1  4956.3 5080.04
Encroach Node=10036.
       1  4942.1 5043.44       1  4942.1 5043.44
Encroach Node=9537.
       1  4947.2  5075.1       1  4947.2  5075.1
Encroach Node=9431.0
       1    4903    5063       1    4903    5063
Encroach Node=9371.0
       1    4903    5063       1    4903    5063
Encroach Node=9311.0
       1    4903    5063       1    4903    5063
Encroach Node=9209.
       1  4940.3  5060.3       1  4940.3  5060.3
Encroach Node=8721.5
       1    4930    5065       1    4930    5065
Encroach Node=7327.
       1 4952.44 5048.41       1 4952.44 5048.41
Encroach Node=7227.2
       1  4953.3  5057.7       1  4953.3  5057.7
Encroach Node=7217.0
       1  4953.3  5057.7       1  4953.3  5057.7
Encroach Node=7206.7
       1    4948  5057.7       1    4948  5057.7
Encroach Node=7100
       1 4957.32 5049.87       1 4957.32 5049.87
Encroach Node=6755.
       1  4947.9  5057.9       1  4947.9  5057.9
Encroach Node=6650.6
       1  4944.6  5058.5       1  4944.6  5058.5
Encroach Node=6610.6
       1  4944.6  5058.5       1  4944.6  5058.5
Encroach Node=6570.6
       1  4944.6  5058.5       1  4944.6  5058.5
Encroach Node=6475.
       1  4931.1 5057.85       1  4931.1 5057.85
Encroach Node=5676.
       1  4935.6  5056.6       1  4935.6  5056.6
Encroach Node=5568.5
       1  4913.3  5051.7       1  4913.3  5051.7
Encroach Node=5523.5
       1  4913.3  5051.7       1  4913.3  5051.7
Encroach Node=5478.5
       1  4913.3  5051.7       1  4913.3  5051.7
Encroach Node=5373.
       1 4915.98 5050.07       1 4915.98 5050.07
Encroach Node=4678.3
       1  4933.6  5039.3       1  4933.6  5039.3
Encroach Node=3202.
       1    4844 5107.63       1    4844 5107.63
Encroach Node=3105.7
       1    4894    5157       1    4894    5157
Encroach Node=3078.7
       1    4847    5157       1    4847    5157
Encroach Node=3051.7
       1  4907.5    5157       1  4907.5    5157
Encroach Node=2935.
       1 4937.97    5153       1 4937.97    5153
Encroach Node=2602.
       1  4899.5 5048.75       1  4899.5 5048.75
Encroach Node=2512.8
       1  4941.8  5050.8       1  4941.8  5050.8
Encroach Node=2499.3
       1  4941.8  5050.8       1  4941.8  5050.8
Encroach Node=2485.8
       1  4941.8  5050.8       1  4941.8  5050.8
Encroach Node=2396.
       1  4939.4 5047.73       1  4939.4 5047.73
Encroach Node=1661.2
       1    4942    5055       1    4942    5055
Encroach Node=1218.
       1  4950.7  5060.7       1  4950.7  5060.7
Encroach Node=1125.0
       1 4950.11 5064.61       1 4950.11 5064.61
Encroach Node=1114.5
       1 4950.11 5064.61       1 4950.11 5064.61
Encroach Node=1104.0
       1 4950.11 5064.61       1 4950.11 5064.61
Encroach Node=1041.8
       1  4936.8  5064.4       1  4936.8  5064.4
Encroach Node=1031.3
       1  4937.2  5063.4       1  4937.2  5063.4
Encroach Node=1020.8
       1  4937.2  5063.4       1  4937.2  5063.4
Encroach Node=895.0
       1  4929.1  5069.1       1  4929.1  5069.1
Encroach Reach=K131-02-00_0009
Encroach Node=22720.9
       1 4129.58 5109.09       0       0       0
Encroach Node=21280.
       1 4524.01 5094.29       0       0       0
Encroach Node=21193.2
       1 4524.01 5094.29       0       0       0
Encroach Node=21151.4
       1 4524.01 5094.29       0       0       0
Encroach Node=21109.5
       1 4524.01 5094.29       0       0       0
Encroach Node=21020.
       1 4524.01 5094.29       0       0       0
Encroach Node=20554.
       1    4500    5068       0       0       0
Encroach Node=20478.0
       1 3613.04 4018.09       0       0       0
Encroach Node=20446.0
       1 3613.04 4018.09       0       0       0
Encroach Node=20414.0
       1 3613.04 4018.09       0       0       0
Encroach Node=20314.
       1 4524.01  5031.2       0       0       0
Encroach Node=19679.
       1 4881.29 5201.52       0       0       0
Encroach Node=19577.8
       1 4881.29 5201.52       0       0       0
Encroach Node=19551.8
       1 4881.29 5201.52       0       0       0
Encroach Node=19525.8
       1 4881.29 5201.52       0       0       0
Encroach Node=19468.
       1 4881.29 5201.52       0       0       0
Encroach Node=18627.
       1 4726.78  5041.5       0       0       0
Encroach Node=18563.1
       1 4726.78  5041.5       0       0       0
Encroach Node=18533.1
       1 4726.78  5041.5       0       0       0
Encroach Node=18503.1
       1 4726.78  5041.5       0       0       0
Encroach Node=18417.
       1 4656.01  5010.7       0       0       0
Encroach Node=17991.
       1 4755.53    5120       0       0       0
Encroach Node=17886.3
       1  4737.9    5100       0       0       0
Encroach Node=17838.8
       1  4737.9 5038.69       0       0       0
Encroach Node=17791.3
       1  4737.9    5100       0       0       0
Encroach Node=17688.
       1    4760    5120       0       0       0
Encroach Node=16029.9
       1  4774.7    5200       0       0       0
Encroach Node=15545.3
       1 4913.46 5063.64       0       0       0
Encroach Node=13933.0
       1    4950  5042.9       0       0       0
Encroach Node=12305.1
       1  4948.1  5048.3       0       0       0
Encroach Node=11553.3
       1    4920  5041.2       0       0       0
Encroach Node=10364.8
       1    4969  5050.1       0       0       0
Encroach Node=10285.5
       1    4900    5100       0       0       0
Encroach Node=10257.5
       1    4900    5100       0       0       0
Encroach Node=10229.5
       1    4900    5100       0       0       0
Encroach Node=10157.0
       1  4959.9 5080.04       0       0       0
Encroach Node=10146.5
       1  4959.9 5080.04       0       0       0
Encroach Node=10136.0
       1  4956.3 5080.04       0       0       0
Encroach Node=10036.
       1  4942.1 5043.44       0       0       0
Encroach Node=9537.
       1  4947.2  5075.1       0       0       0
Encroach Node=9431.0
       1    4903    5063       0       0       0
Encroach Node=9371.0
       1    4903    5063       0       0       0
Encroach Node=9311.0
       1    4903    5063       0       0       0
Encroach Node=9209.
       1  4940.3  5060.3       0       0       0
Encroach Node=8721.5
       1    4930    5065       0       0       0
Encroach Node=7327.
       1 4952.44 5048.41       0       0       0
Encroach Node=7227.2
       1  4953.3  5057.7       0       0       0
Encroach Node=7217.0
       1  4953.3  5057.7       0       0       0
Encroach Node=7206.7
       1    4948  5057.7       0       0       0
Encroach Node=7100
       1 4957.32 5049.87       0       0       0
Encroach Node=6755.
       1  4947.9  5057.9       0       0       0
Encroach Node=6650.6
       1  4944.6  5058.5       0       0       0
Encroach Node=6610.6
       1  4944.6  5058.5       0       0       0
Encroach Node=6570.6
       1  4944.6  5058.5       0       0       0
Encroach Node=6475.
       1  4931.1 5057.85       0       0       0
Encroach Node=5676.
       1  4935.6  5056.6       0       0       0
Encroach Node=5568.5
       1  4913.3  5051.7       0       0       0
Encroach Node=5523.5
       1  4913.3  5051.7       0       0       0
Encroach Node=5478.5
       1  4913.3  5051.7       0       0       0
Encroach Node=5373.
       1 4915.98 5050.07       0       0       0
Encroach Node=4678.3
       1  4933.6  5039.3       0       0       0
Encroach Node=3202.
       1    4844 5107.63       0       0       0
Encroach Node=3105.7
       1    4894    5157       0       0       0
Encroach Node=3078.7
       1    4847    5157       0       0       0
Encroach Node=3051.7
       1  4907.5    5157       0       0       0
Encroach Node=2935.
       1 4937.97    5153       0       0       0
Encroach Node=2602.
       1  4899.5 5048.75       0       0       0
Encroach Node=2512.8
       1  4941.8  5050.8       0       0       0
Encroach Node=2499.3
       1  4941.8  5050.8       0       0       0
Encroach Node=2485.8
       1  4941.8  5050.8       0       0       0
Encroach Node=2396.
       1  4939.4 5047.73       0       0       0
Encroach Node=1661.2
       1    4942    5055       0       0       0
Encroach Node=1218.
       1  4950.7  5060.7       0       0       0
Encroach Node=1125.0
       1 4950.11 5064.61       0       0       0
Encroach Node=1114.5
       1 4950.11 5064.61       0       0       0
Encroach Node=1104.0
       1 4950.11 5064.61       0       0       0
Encroach Node=1041.8
       1  4936.8  5064.4       0       0       0
Encroach Node=1031.3
       1  4937.2  5063.4       0       0       0
Encroach Node=1020.8
       1  4937.2  5063.4       0       0       0
Encroach Node=895.0
       1  4929.1  5069.1       0       0       0
Computation Interval=1HOUR
Output Interval=1HOUR
Run HTab= 0
Run UNet= 0
Run PostProcess= 0
UNET Theta= 1
UNET ZTol= 0.02
UNET ZSATol= 0.1
UNET MxIter= 20
UNET MaxInSteps= 20
UNET DtIC= 0
UNET DtMin= 0
UNET MaxCRTS= 20
UNET WFStab= 2
UNET SFStab= 1
UNET WFX= 1
UNET SFX= 1
UNET Convert EG Bridges=-1
UNET Use Existing IB Tables=-1
Instantaneous Interval=1HOUR
DSS File=dss
Write IC File= 0
Write Velocity= 0
Write Detailed= 0

--- K131-02-00.p01 (plan) ---

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Plan Title=FEMA Effective June 2007
Short Identifier=FEMAeff0607
Geom File=g01
Flow File=f01
Encroach Param=-1 ,0,0, 2

--- K131-02-00.p04 (plan) ---

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Plan Title=Storage Routing
Short Identifier=Store_Rout
Geom File=g01
Flow File=f04
Encroach Param=-1 ,0,0, 0

--- K131-02-00.f02 (steady flow) ---

Flow Title=Floodway
Version=Version 3.0.1  Mar 2001
Number of Profiles= 2
Profile Names=1PCT_100yr, 1PCTFloodway_100yrFW
River Rch & RM=K131-02-00,K131-02-00_0009,22720.9
    2170    2170
River Rch & RM=K131-02-00,K131-02-00_0009,18563.1
    2250    2250
River Rch & RM=K131-02-00,K131-02-00_0009,16029.9
    2870    2870
River Rch & RM=K131-02-00,K131-02-00_0009,15545.3
    3000    3000
River Rch & RM=K131-02-00,K131-02-00_0009,13933.0
    3130    3130
River Rch & RM=K131-02-00,K131-02-00_0009,12305.1
    3200    3200
River Rch & RM=K131-02-00,K131-02-00_0009,11553.3
    3310    3310
River Rch & RM=K131-02-00,K131-02-00_0009,10157.0
    3400    3400
River Rch & RM=K131-02-00,K131-02-00_0009,8721.5
    3660    3660
River Rch & RM=K131-02-00,K131-02-00_0009,7227.2
    3750    3750
River Rch & RM=K131-02-00,K131-02-00_0009,5568.5
    3900    3900
River Rch & RM=K131-02-00,K131-02-00_0009,4678.3
    4140    4140
River Rch & RM=K131-02-00,K131-02-00_0009,1661.2
    4254    4254
Boundary for River Rch & Prof#=K131-02-00,K131-02-00_0009, 1
Up Type= 0
Dn Type= 3
Dn Slope=.0018
Boundary for River Rch & Prof#=K131-02-00,K131-02-00_0009, 2
Up Type= 0
Dn Type= 3
Dn Slope=.0018
DSS Import GetInterval= 0
DSS Import GetPeak= 0
DSS Import FillOption= 0

--- K131-02-00.f01 (steady flow) ---

Flow Title=FEMA Effective June 2007
Version=Version 3.0.1  Mar 2001
Number of Profiles= 4
Profile Names=10PCT_10yr, 2PCT_50yr, 1PCT_100yr, 0.2PCT_500yr
River Rch & RM=K131-02-00,K131-02-00_0009,22720.9
    1270    1950    2170    3400
River Rch & RM=K131-02-00,K131-02-00_0009,18563.1
    1300    2000    2250    3500
River Rch & RM=K131-02-00,K131-02-00_0009,16029.9
    1600    2390    2870    4240
River Rch & RM=K131-02-00,K131-02-00_0009,15545.3
    1670    2530    3000    4430
River Rch & RM=K131-02-00,K131-02-00_0009,13933.0
    1750    2690    3130    4620
River Rch & RM=K131-02-00,K131-02-00_0009,12305.1
    1790    2760    3200    4710
River Rch & RM=K131-02-00,K131-02-00_0009,11553.3
    1850    2890    3310    4870
River Rch & RM=K131-02-00,K131-02-00_0009,10157.0
    1900    3000    3400    5000
River Rch & RM=K131-02-00,K131-02-00_0009,8721.5
    2480    3210    3660    5470
River Rch & RM=K131-02-00,K131-02-00_0009,7227.2
    2700    3280    3750    5630
River Rch & RM=K131-02-00,K131-02-00_0009,5568.5
    3100    3400    3900    5900
River Rch & RM=K131-02-00,K131-02-00_0009,4678.3
    2530    3530    4140    6100
River Rch & RM=K131-02-00,K131-02-00_0009,1661.2
    2297    3597    4254    6195
Boundary for River Rch & Prof#=K131-02-00,K131-02-00_0009, 1
Up Type= 0
Dn Type= 3
Dn Slope=.0018
Boundary for River Rch & Prof#=K131-02-00,K131-02-00_0009, 2
Up Type= 0
Dn Type= 3
Dn Slope=.0018
Boundary for River Rch & Prof#=K131-02-00,K131-02-00_0009, 3
Up Type= 0
Dn Type= 3
Dn Slope=.0018
Boundary for River Rch & Prof#=K131-02-00,K131-02-00_0009, 4
Up Type= 0
Dn Type= 3
Dn Slope=.0018
DSS Import GetInterval= 0
DSS Import GetPeak= 0
DSS Import FillOption= 0

--- K131-02-00.f04 (steady flow) ---

Flow Title=Storage Routing
Version=Version 3.0.1  Mar 2001
Number of Profiles= 7
Profile Names=0.25*10% flood, 0.50*10%flood, 10% flood, 2% flood, 1% flood, 0.2%flood, 1.25*0.2% flood
River Rch & RM=K131-02-00,K131-02-00_0009,22720.9
      76     153     305     510     645     935    1169
River Rch & RM=K131-02-00,K131-02-00_0009,20478.0
      84     168     336     563     704    1030    1288
River Rch & RM=K131-02-00,K131-02-00_0009,16029.9
     112     224     448     728     898    1285    1606
River Rch & RM=K131-02-00,K131-02-00_0009,13933.0
     160     320     640    1003    1216    1694    2118
River Rch & RM=K131-02-00,K131-02-00_0009,12305.1
     222     443     886    1341    1603    2177    2721
River Rch & RM=K131-02-00,K131-02-00_0009,11553.3
     265     530    1060    1571    1865    2500    3125
River Rch & RM=K131-02-00,K131-02-00_0009,10285.5
     308     616    1232    1802    2120    2808    3510
River Rch & RM=K131-02-00,K131-02-00_0009,9431.0
     349     698    1395    2013    2355    3090    3863
River Rch & RM=K131-02-00,K131-02-00_0009,8721.5
     364     729    1457    2099    2453    3210    4013
River Rch & RM=K131-02-00,K131-02-00_0009,7227.2
     405     810    1620    2325    2710    3526    4408
River Rch & RM=K131-02-00,K131-02-00_0009,5568.5
     450     900    1800    2572    2991    3868    4835
River Rch & RM=K131-02-00,K131-02-00_0009,3105.7
     501    1002    2003    2850    3305    4248    5310
River Rch & RM=K131-02-00,K131-02-00_0009,1661.2
     555    1110    2219    3145    3639    4650    5813
Boundary for River Rch & Prof#=K131-02-00,K131-02-00_0009, 1
Up Type= 0
Dn Type= 3
Dn Slope=.0006
Boundary for River Rch & Prof#=K131-02-00,K131-02-00_0009, 2
Up Type= 0
Dn Type= 3
Dn Slope=.0006
Boundary for River Rch & Prof#=K131-02-00,K131-02-00_0009, 3
Up Type= 0
Dn Type= 3
Dn Slope=.0006
Boundary for River Rch & Prof#=K131-02-00,K131-02-00_0009, 4
Up Type= 0
Dn Type= 3
Dn Slope=.0006
DSS Import GetInterval= 0
DSS Import GetPeak= 0
DSS Import FillOption= 0

--- K131-02-00.g01 (geometry) ---

Geom Title=K131-02-00 June 2007
Version=Version 3.0.1  Mar 2001

River Reach=K131-02-00      ,K131-02-00_0009
Reach XY= 30
      3059798.57     13946249.91        3059481.       13946149.
       3059406.5       13945095.      3059439.22     13944856.74
       3059718.5       13944612.      3059832.08     13943996.89
      3060207.08     13943796.37       3060438.7     13943843.74
      3060660.25       13943366.      3061573.04     13942715.44
      3061741.79     13942361.27      3061573.25       13942204.
      3061625.13     13941631.41      3061471.65     13941330.71
      3061580.42     13940517.95      3062160.28     13940053.53
      3062197.08     13939863.95      3063606.71     13938413.34
      3063873.47     13938241.03      3064642.22     13938584.08
      3064954.72     13938546.58      3065343.54     13938243.03
      3065575.55     13937837.56      3065926.31     13937705.26
      3066340.14     13937785.47      3068885.28     13935371.58
      3069643.35     13934947.02       3071802.2     13935089.38
      3073551.33     13935756.91      3074045.75       13935692.

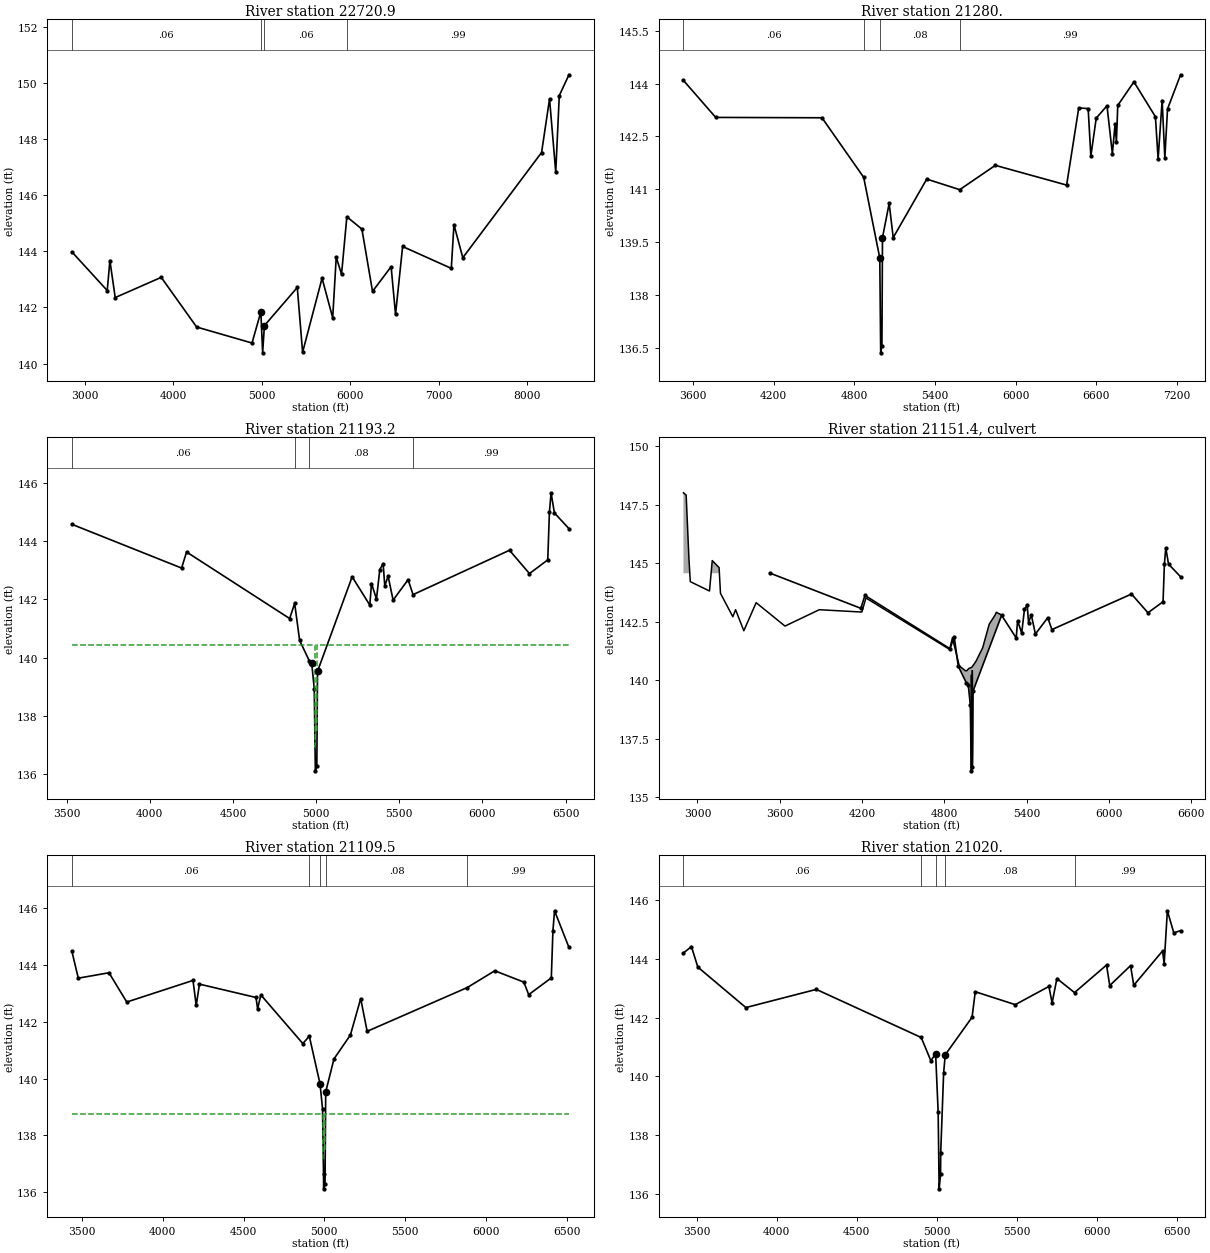
Type RM Length L Ch R = 1 ,22720.9 ,1500,1440.9,1400
BEGIN DESCRIPTION:
K131-02-04-X11-interp
END DESCRIPTION:
XS GIS Cut Line= 4
      3061531.49     13945512.87       3059702.5     13946011.13
      3059501.97     13946630.93      3057751.97     13949152.63
#Sta/Elev= 30
  2856.1  143.98  3256.1   142.6  3286.1  143.67  3346.1  142.35  3866.1  143.07
  4266.1   141.3  4891.7  140.73  4991.7  141.84  5011.7  140.38  5031.7  141.35
  5403.2  142.71  5463.2   140.4  5683.2  143.04  5803.2  141.63  5843.2  143.79
  5903.2  143.18  5963.2  145.23  6133.2  144.79  6253.2  142.57  6463.2  143.45
  6513.2  141.75  6593.2  144.17  7143.2  143.39  7173.2  144.95  7273.2  143.77
  8163.2  147.52  8253.2  149.43  8323.2  146.82  8363.2  149.55  8472.6  150.29
#Mann= 4 ,-1 , 0
  2856.1     .06       0  4991.7     .05       0  5031.7     .06       0
  5963.2     .99       0
Bank Sta=4991.7,5031.7
XS Rating Curve= 0
Exp/Cntr=.3,.1

Type RM Length L Ch R = 1 ,21280.  ,50.3,86.8,88
BEGIN DESCRIPTION:
RD NORTH OF AZALEA_US - XS 4
END DESCRIPTION:
XS GIS Cut Line= 4
      3060823.43      13945389.2       3059523.8      13944957.3
      3059314.61     13944953.03      3057239.49     13944534.42
#Sta/Elev= 30
  3530.1  144.09  3770.1  143.04  4560.1  143.03  4870.1  141.34 4989.85  139.05
 4996.51  136.36 5005.69  136.55 5009.91  139.63  5059.6   140.6  5089.6  139.63
  5338.9  141.29    5584  140.99  5848.9  141.68  6378.9  141.12  6468.9  143.31
  6538.9  143.29  6558.9  141.94  6598.9  143.02  6678.9  143.37  6718.9  142.01
  6738.9  142.84  6748.9  142.34  6758.9  143.38  6878.9  144.05  7038.9  143.06
  7058.9  141.86  7088.9  143.52  7108.9  141.89  7128.9  143.28  7225.8  144.25
#Mann= 4 ,-1 , 0
  3530.1     .06       0  4870.1      .1       0 4989.85     .08       0
    5584     .99       0
Bank Sta=4989.85,5009.91
XS Rating Curve= 0
Exp/Cntr=.5,.3

Type RM Length L Ch R = 1 ,21193.2 ,85,83.7,77.9
BEGIN DESCRIPTION:
Upstream Section of Bridge/Culvert/Weir
END DESCRIPTION:
XS GIS Cut Line= 5
      3060830.87      13945296.1      3059459.29     13944899.88
      3059421.12      13944843.5      3059343.05     13944674.34
      3058607.71     13943593.06
#Sta/Elev= 30
  3531.1  144.57  4191.1  143.07  4221.1  143.62  4841.1  141.34  4871.1  141.86
  4901.1  140.59  4959.2  139.89  4973.6  139.81  4988.9  138.94  4995.6  136.12
  5004.5  136.28  5008.6  139.53  5216.9  142.77  5323.2   141.8  5333.2  142.54
  5363.2  142.01  5383.2  143.02  5403.2  143.22  5413.2  142.46  5433.2  142.79
  5463.2  141.97  5553.2  142.67  5583.2  142.16  6163.2  143.68  6283.2  142.88
  6393.2  143.35  6403.2  144.98  6413.2  145.65  6433.2  144.96  6520.8  144.42
#Mann= 4 ,-1 , 0
  3531.1     .06       0  4871.1      .1       0  4959.2     .08       0
  5583.2     .99       0
#XS Ineff= 2 , 0
       0 4993.79  140.44    5006       0  140.44
Permanent Ineff=
       F       F
Bank Sta=4973.6,5008.6
XS Rating Curve= 0
Exp/Cntr=.5,.3

Type RM Length L Ch R = 2 ,21151.4 ,,,
BEGIN DESCRIPTION:
EAST END OF ROAD NORTH OF AZALEA WAY
Structure ID: K131-02-00-S16
END DESCRIPTION:
Bridge Culvert--1,0,-1,-1, 0
Deck Dist Width WeirC Skew NumUp NumDn MinLoCord MaxHiCord MaxSubmerge Is_Ogee
10,42,2.6,0, 46, 46, , , .95, 0, ,,,
  2898.3  2918.3  2938.3  2948.3  3088.3  3108.3  3158.3  3168.3  3258.3  3278.3
  3338.3  3428.3  3638.3  3888.3  4198.3  4228.3  4248.3  4838.3  4858.3  4908.3
  4952.9  4955.4  4959.2  4962.9  4973.6  4978.5  4988.9  4994.3  4995.2  4995.6
    5000  5000.1  5004.5  5004.7  5005.3  5006.9  5008.6  5030.7  5059.8  5078.7
  5111.9  5126.3  5161.5  5170.2    5178  5216.9
  148.01  147.91  145.21  144.21  143.81  145.11  144.81  143.71  142.71  143.01
  142.11  143.31  142.31  143.01  142.91  143.51  143.44  141.31  141.81  140.61
   140.4   140.4   140.4   140.4  140.47   140.5  140.52  140.54  140.54  140.54
  140.55  140.55  140.59  140.59  140.59  140.61  140.62  140.81  141.16  141.38
  142.08  142.39  142.71  142.79   142.9  142.78
                                                                                
                                                                                
                                                                                
                                                                                
                                                
  2898.3  2918.3  2938.3  2948.3  3088.3  3108.3  3158.3  3168.3  3258.3  3278.3
  3338.3  3428.3  3638.3  3888.3  4198.3  4228.3  4248.3  4838.3  4858.3  4908.3
  4952.9  4955.4  4959.2  4962.9  4973.6  4978.5  4988.9  4994.3  4995.2  4995.6
    5000  5000.1  5004.5  5004.7  5005.3  5006.9  5008.6  5030.7  5059.8  5078.7
  5111.9  5126.3  5161.5  5170.2    5178  5216.9
  148.01  147.91  145.21  144.21  143.81  145.11  144.81  143.71  142.71  143.01
  142.11  143.31  142.31  143.01  142.91  143.51  143.44  141.31  141.81  140.61
   140.4   140.4   140.4   140.4  140.47   140.5  140.52  140.54  140.54  140.54
  140.55  140.55  140.59  140.59  140.59  140.61  140.62  140.81  141.16  141.38
  142.08  142.39  142.71  142.79   142.9  142.78
                                                                                
                                                                                
                                                                                
                                                                                
                                                
BR Coef= 1 , 0 , 0 ,1.25, 0 ,,,.8,0,2,0,
WSPro=,,,, 1 ,,,, 0 ,,,, 0 ,,,,-1 ,-1 ,-1 , 0 , 0 , 0 , 0 , 0
Culvert=1,4,,42,.024,.9,1,2,3,136.23,4996.5,136.55,4996.5,Culvert #1  , 0 ,10
Culvert Bottom n=.024
Culvert=1,4,,42,.024,.9,1,2,3,136.43,5003.5,136.55,5003.5,Culvert #2  , 0 ,10
Culvert Bottom n=.024
BC Design=,, 0 ,, 0 ,,,,,,

Type RM Length L Ch R = 1 ,21109.5 ,75.6,89.5,91
BEGIN DESCRIPTION:
Downstream Section of Bridge/Culvert/Weir
END DESCRIPTION:
XS GIS Cut Line= 5
 3060976.493275213945273.9530669      3059517.35     13944848.75
      3059482.62     13944797.45      3059404.54     13944628.27
      3058668.28     13943545.63
#Sta/Elev= 30
  3437.1  144.48  3477.1  143.53  3667.1  143.72  3777.1  142.69  4187.1  143.45
  4207.1  142.57  4227.1  143.32  4577.1  142.85  4587.1  142.45  4607.1  142.94
  4867.1  141.23  4907.1  141.49  4973.6  139.81  4988.9  138.94  4995.2  136.64
  4995.6  136.12  5004.5  136.28  5008.6  139.53  5059.8  140.69  5161.5  141.53
  5225.2  142.81  5265.2  141.66  5885.2   143.2  6055.2  143.79  6235.2  143.39
  6265.2  142.95  6405.2  143.54  6415.2   145.2  6425.2   145.9  6514.5  144.61
#Mann= 5 ,-1 , 0
  3437.1     .06       0  4907.1      .1       0  4973.6     .08       0
  5008.6     .08       0  5885.2     .99       0
#XS Ineff= 2 , 0
       0 4993.79  138.75    5006       0  138.75
Permanent Ineff=
       F       F
Bank Sta=4973.6,5008.6
XS Rating Curve= 0
Exp/Cntr=.5,.3

Type RM Length L Ch R = 1 ,21020.  ,500.4,466,384.8
BEGIN DESCRIPTION:
RD NORTH OF AZALEA_DS - XS 1
END DESCRIPTION:
XS GIS Cut Line= 4
       3061069.6      13945225.5      3059592.11     13944807.88
      3059534.48     13944705.41      3058683.37     13943528.41
#Sta/Elev= 30
  3416.6   144.2  3466.6  144.42  3506.6  143.72  3806.6  142.34  4246.6  142.96
    4902  141.32    4962  140.53    4992  140.76 5007.84  138.77 5014.03  136.16
 5022.89  136.67 5023.68  137.39    5042  140.11    5052  140.73  5219.6  142.01
  5239.6  142.88  5489.6  142.44  5699.6  143.06  5719.6   142.5  5749.6  143.33
  5859.6  142.85  6059.6  143.79  6079.6  143.09  6209.6  143.77  6229.6   143.1
  6409.6  144.27  6419.6  143.84  6439.6  145.64  6479.6  144.89    6522  144.96
#Mann= 5 ,-1 , 0
  3416.6     .06       0    4902      .1       0    4992     .08       0
    5052     .08       0  5859.6     .99       0
Bank Sta=4992,5052
XS Rating Curve= 0
Exp/Cntr=.3,.1

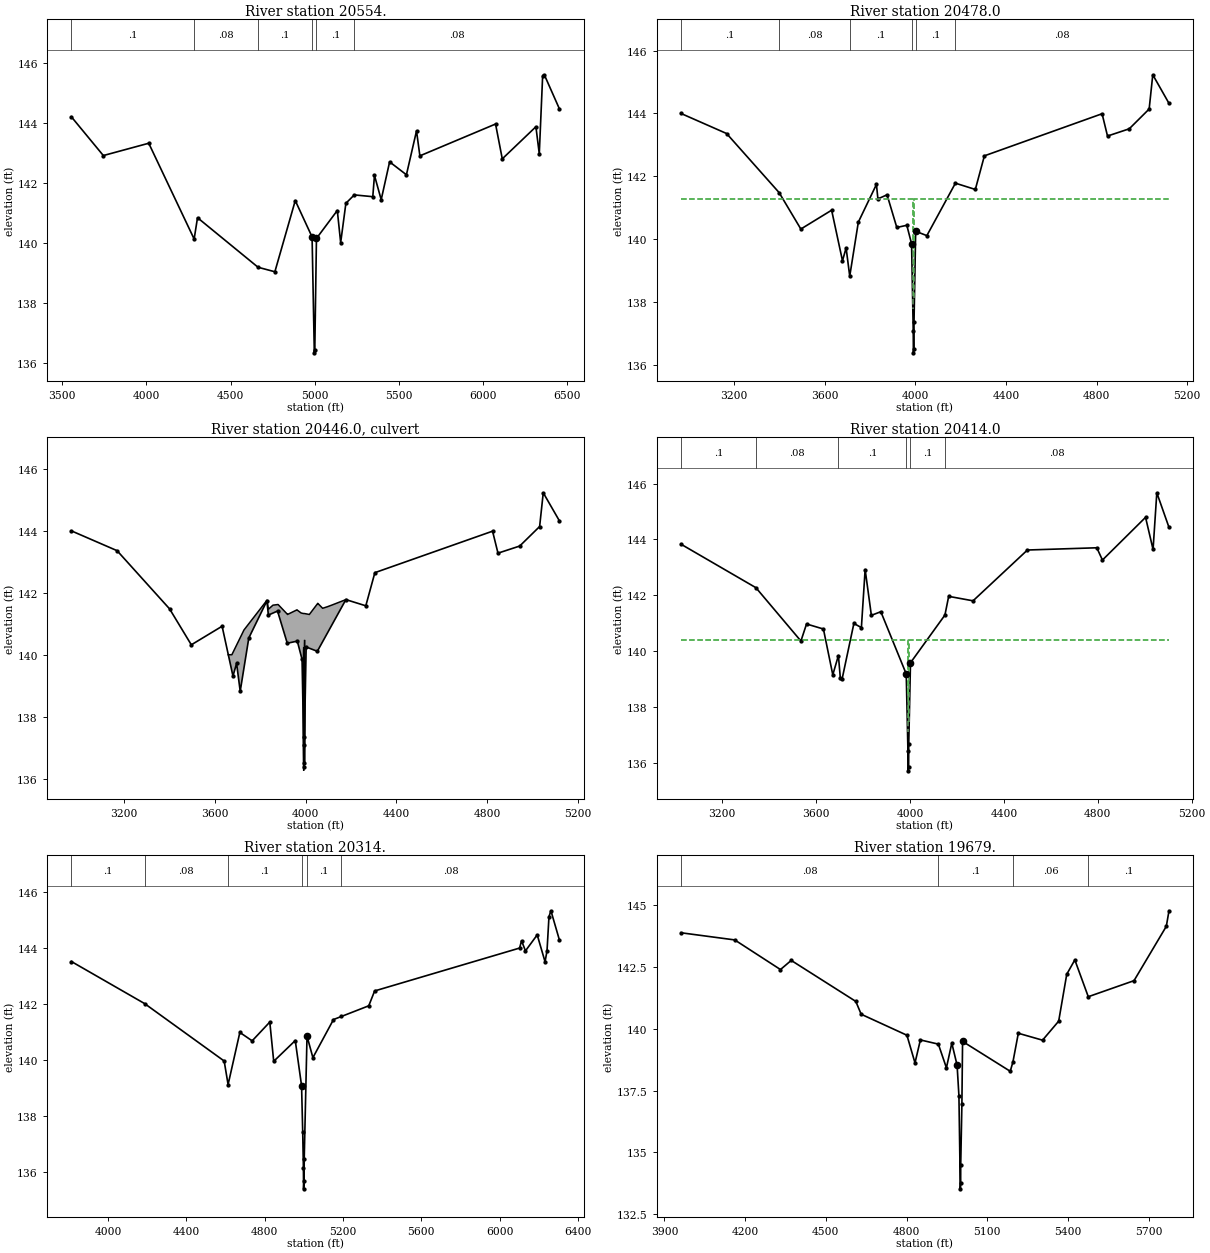
Type RM Length L Ch R = 1 ,20554.  ,152.9,76,75
BEGIN DESCRIPTION:
AZALEA_US - XS 4
END DESCRIPTION:
XS GIS Cut Line= 4
      3061229.39      13944506.8      3059952.87     13944395.89
      3059624.13     13944357.47       3058674.3     13943484.39
#Sta/Elev= 30
  3553.6  144.21  3743.6  142.92  4013.6  143.33  4283.6  140.14  4303.6  140.85
  4663.6   139.2  4763.6  139.05  4884.9  141.42  4984.9  140.21 4998.24  136.35
 5001.04  136.46 5010.89  140.16  5134.9  141.09  5154.9  140.02  5185.9  141.33
  5235.9  141.61  5345.9  141.55  5355.9  142.26  5395.9  141.45  5445.9  142.71
  5545.9  142.28  5605.9  143.74  5625.9  142.91  6075.9  143.97  6115.9  142.81
  6315.9  143.88  6335.9  142.98  6355.9  145.57  6365.9  145.61    6456  144.47
#Mann= 6 ,-1 , 0
  3553.6      .1       0  4283.6     .08       0  4663.6      .1       0
  4984.9     .06       0 5010.89      .1       0  5235.9     .08       0
Bank Sta=4984.9,5010.89
XS Rating Curve= 0
Exp/Cntr=.5,.3

Type RM Length L Ch R = 1 ,20478.0 ,34.2,64,75
BEGIN DESCRIPTION:
Upstream Section of Bridge/Culvert/Weir
END DESCRIPTION:
XS GIS Cut Line= 6
 3061023.6759375 13944419.578355      3060070.03     13944194.35
      3059860.22     13944240.52      3059815.98     13944273.48
      3059752.32     13944315.42      3058678.69      13943465.1
#Sta/Elev= 30
2966.611     1443168.187  143.363399.791  141.483495.627  140.323631.396  140.92
3679.314  139.313695.286  139.723711.259  138.823749.194  140.543829.058  141.74
3835.527  141.283875.858  141.413918.904  140.373963.069  140.443984.073  139.85
3991.341  137.093992.059  136.383994.295   136.53994.775  137.354002.122  140.25
4051.398  140.114177.423  141.784265.272  141.584305.205  142.654824.317  143.99
4848.276  143.284944.113  143.515031.963  144.145047.936  145.235119.493  144.32
#Mann= 6 ,-1 , 0
2966.611      .1       03399.791     .08       03711.259      .1       0
3984.073     .06       04002.122      .1       04177.423     .08       0
#XS Ineff= 2 , 0
       03989.512  141.293996.771       0  141.29
Permanent Ineff=
       F       F
Bank Sta=3984.073,4002.122
XS Rating Curve= 0
Skew Angle= 37
Exp/Cntr=.5,.3

Type RM Length L Ch R = 2 ,20446.0 ,,,
BEGIN DESCRIPTION:
AZALEA WAY; Adjust top of road on left side so the lowest point would be 140'(based off of the contour file) VRR
Structure ID: K131-02-00-S15
END DESCRIPTION:
Bridge Culvert--1,0,-1,-1, 0
Deck Dist Width WeirC Skew NumUp NumDn MinLoCord MaxHiCord MaxSubmerge Is_Ogee
10,44,2.6,37, 30, 30, , , .95, 0, ,,,
3658.4693666.4563674.442 3727.953829.4573835.5273855.6523875.8583878.6533918.904
3919.7833961.8713963.0693979.5213984.0733991.3413991.8993992.0593993.2573994.295
3994.4553994.7754002.1224016.1784051.3984053.3144074.8784095.8824114.3314177.423
     140     140     140   140.8  141.76  141.47   141.6  141.62  141.62  141.31
   141.3  141.45  141.44  141.35  141.34  141.33  141.33  141.33  141.33  141.33
  141.33  141.33  141.32   141.3  141.64  141.66   141.5  141.55   141.6  141.78
                                                                                
                                                                                
                                                                                
3658.4693666.4563674.442 3727.953829.4573835.5273855.6523875.8583878.6533918.904
3919.7833961.8713963.0693979.5213984.0733991.3413991.8993992.0593993.2573994.295
3994.4553994.7754002.1224016.1784051.3984053.3144074.8784095.8824114.3314177.423
     140     140     140   140.8  141.76  141.47   141.6  141.62  141.62  141.31
   141.3  141.45  141.44  141.35  141.34  141.33  141.33  141.33  141.33  141.33
  141.33  141.33  141.32   141.3  141.64  141.66   141.5  141.55   141.6  141.78
                                                                                
                                                                                
                                                                                
BR Coef= 1 , 0 , 0 ,1.25, 0 ,,,.8,0,2,0,
WSPro=,,,, 1 ,,,, 0 ,,,, 0 ,,,,-1 ,-1 ,-1 , 0 , 0 , 0 , 0 , 0
Culvert=1,4,,44,.024,.9,1,2,3,136.25,3991.1,136.13,3991.1,Culvert #1  , 0 ,10
Culvert Bottom n=.024
Culvert=1,4,,44,.024,.9,1,2,3,136.48,3995.17,136.09,3995.17,Culvert #2  , 0 ,10
Culvert Bottom n=.024
BC Design=,, 0 ,, 0 ,,,,,,

Type RM Length L Ch R = 1 ,20414.0 ,77.8,100,101
BEGIN DESCRIPTION:
Downstream Section of Bridge/Culvert/Weir
END DESCRIPTION:
XS GIS Cut Line= 6
      3060961.96      13944365.7       3060061.3      13944166.1
      3059847.75       13944208.      3059805.32      13944239.6
      3059759.44      13944269.9       3058693.5      13943433.3
#Sta/Elev= 30
3024.353  143.833343.807  142.273535.479  140.363559.438  140.973631.316  140.79
3671.247  139.153695.207  139.843703.193  139.053711.179  139.013761.094  140.99
3793.039  140.843809.012  142.923835.527  141.283875.858  141.413984.073  139.18
3991.341  136.423992.059  135.713994.295  135.833994.775  136.684002.122  139.58
4148.832  141.294164.804  141.964268.627   141.84500.231  143.624795.726   143.7
4819.685  143.265003.372  144.795035.317  143.64 5051.29  145.675103.201  144.43
#Mann= 6 ,-1 , 0
3024.353      .1       03343.807     .08       03695.207      .1       0
3984.073     .08       04002.122      .1       04148.832     .08       0
#XS Ineff= 2 , 0
       03989.512   140.43996.771       0   140.4
Permanent Ineff=
       F       F
Bank Sta=3984.073,4002.122
XS Rating Curve= 0
Skew Angle= 37
Exp/Cntr=.5,.3

Type RM Length L Ch R = 1 ,20314.  ,572.2,635,782.9
BEGIN DESCRIPTION:
AZALEA_DS - XS 1
END DESCRIPTION:
XS GIS Cut Line= 5
      3060922.97      13944344.9      3060038.25      13944082.1
      3059846.14      13944137.6      3059700.98     13944141.87
      3058719.04     13943411.82
#Sta/Elev= 30
  3813.4  143.52    4187  142.02  4593.4  139.97  4613.4  139.13  4673.4  140.99
  4736.3  140.69  4826.3  141.36  4846.3  139.96  4956.3   140.7 4988.48  139.09
 4994.33  137.43 4997.83  136.17 4998.76  135.41 5001.46   135.7 5002.05  136.48
  5016.3  140.86  5046.3  140.09  5151.5  141.45    5192  141.56  5331.5  141.94
  5361.5  142.47  6101.5     144  6111.5  144.26  6131.5   143.9  6191.5  144.47
  6231.5  143.51  6241.5   143.9  6251.5  145.12  6261.5  145.33  6305.1  144.28
#Mann= 6 ,-1 , 0
  3813.4      .1       0    4187     .08       0  4613.4      .1       0
 4988.48     .08       0  5016.3      .1       0    5192     .08       0
Bank Sta=4988.48,5016.3
XS Rating Curve= 0
Exp/Cntr=.3,.1

Type RM Length L Ch R = 1 ,19679.  ,29.8,101.2,103
BEGIN DESCRIPTION:
VALKA_US - XS 4
END DESCRIPTION:
XS GIS Cut Line= 4
      3061038.12      13944407.2      3060234.64     13943887.84
      3060283.74     13943738.42      3060162.98      13943048.9
#Sta/Elev= 30
  3961.3  143.89  4161.3   143.6  4331.3   142.4  4371.3  142.77  4611.3  141.11
  4631.3  140.59  4801.3  139.74  4831.3  138.62  4851.3  139.55  4918.1  139.38
  4948.1  138.42  4968.1  139.42 4987.72  138.53 4994.56  137.29 4999.74  133.52
    5001  133.75 5001.21  134.49 5005.59  136.95  5008.1  139.49  5185.3  138.28
  5195.3  138.66  5215.3  139.82  5305.3  139.54  5365.3  140.31  5395.3  142.21
  5425.3  142.79  5475.3   141.3  5645.3  141.95  5765.3  144.15  5775.3  144.78
#Mann= 4 ,-1 , 0
  3961.3     .08       0  4918.1      .1       0  5195.3     .06       0
  5475.3      .1       0
Bank Sta=4987.72,5008.1
XS Rating Curve= 0
Exp/Cntr=.5,.3

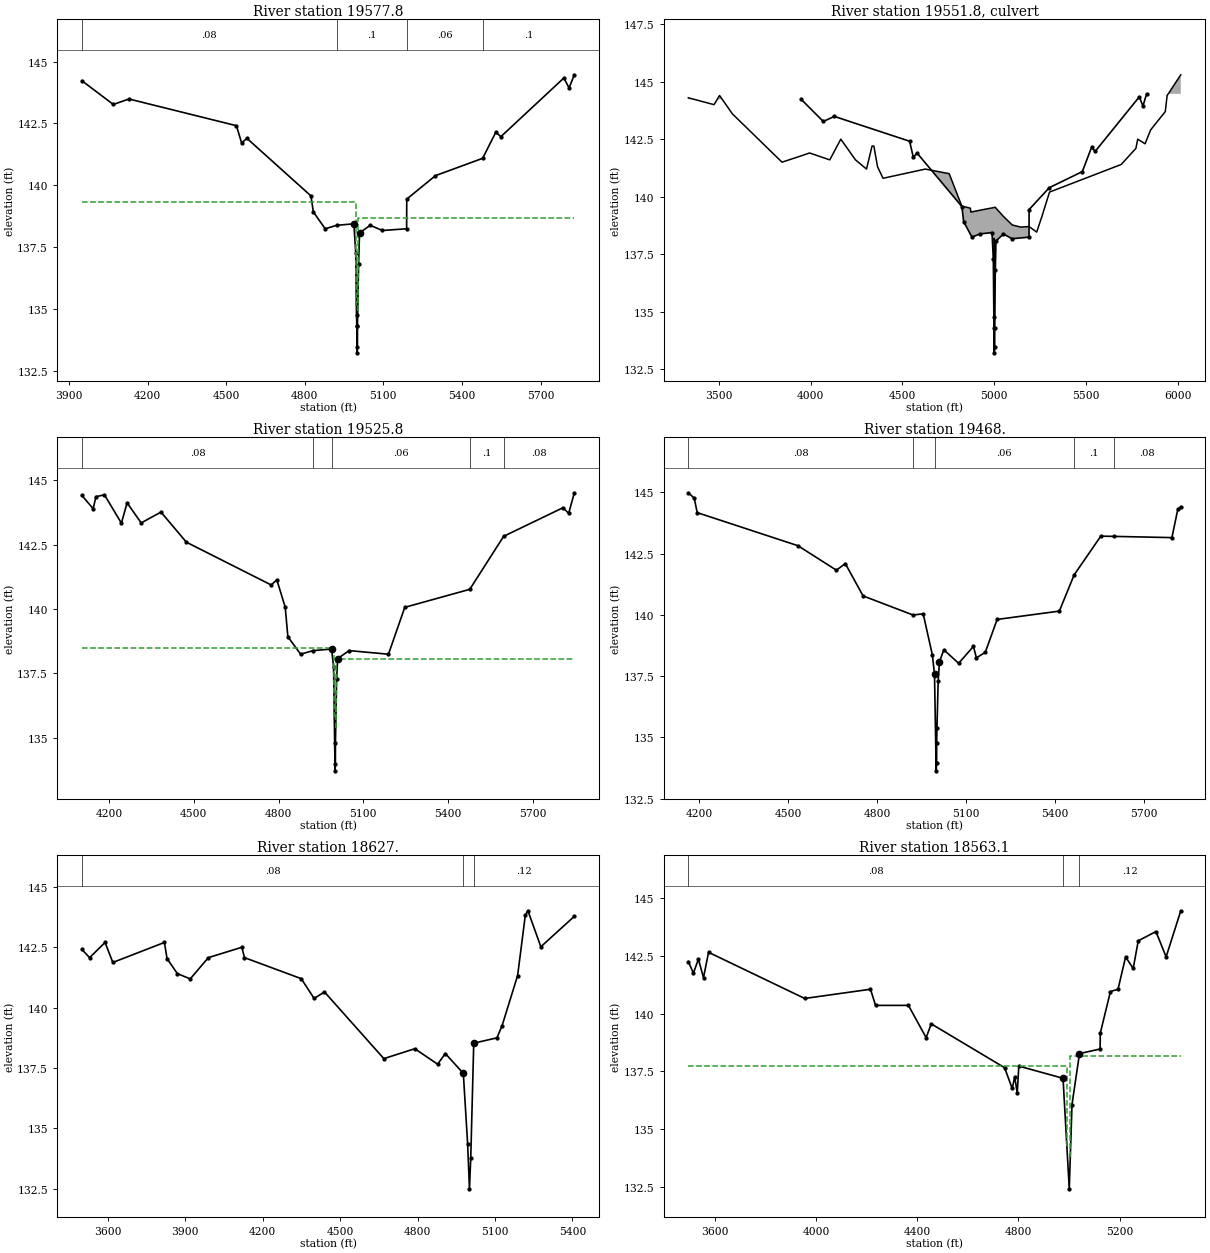
Type RM Length L Ch R = 1 ,19577.8 ,45.1,52,61.4
BEGIN DESCRIPTION:
Upstream Section of Bridge/Culvert/Weir
END DESCRIPTION:
XS GIS Cut Line= 6
      3061131.23     13944448.25      3060313.09     13943910.06
      3060348.95       13943864.      3060372.37     13943805.88
      3060369.76     13943556.18      3060247.45      13943040.5
#Sta/Elev= 30
  3949.1  144.23  4069.1  143.27  4129.1  143.49  4539.1  142.41  4559.1  141.71
  4579.1   141.9  4823.6  139.57  4832.9  138.92  4878.1  138.24    4922  138.38
  4987.6  138.44  4994.6  137.27  4997.6  134.77  4998.8   134.3  4999.9  133.22
  5001.1  133.47  5001.3  134.31  5005.5   136.8  5009.1  138.07  5049.8  138.38
  5096.2  138.17  5188.9  138.24  5189.4  139.44  5299.1  140.39  5479.1  141.09
  5529.1  142.14  5549.1  141.97  5789.1  144.34  5809.1  143.94  5829.1  144.47
#Mann= 4 ,-1 , 0
  3949.1     .08       0    4922      .1       0  5189.4     .06       0
  5479.1      .1       0
#XS Ineff= 2 , 0
       0 4997.31  139.33  5002.3       0  138.68
Permanent Ineff=
       F       F
Bank Sta=4987.6,5009.1
XS Rating Curve= 0
Exp/Cntr=.5,.3

Type RM Length L Ch R = 2 ,19551.8 ,,,
BEGIN DESCRIPTION:
VALKA ROAD; Culvert survey points inverted-checked by VRR
Structure ID: K131-02-00-S14
END DESCRIPTION:
Bridge Culvert--1,0,-1,-1, 0
Deck Dist Width WeirC Skew NumUp NumDn MinLoCord MaxHiCord MaxSubmerge Is_Ogee
10,32,2.6,0, 57, 57, , , .95, 0, ,,,
  3334.4  3474.4  3504.4  3574.4  3844.4  3954.4  3994.4  4104.4  4164.4  4244.4
  4304.4  4334.4  4344.4  4364.4  4394.4  4624.4  4754.4  4819.2  4823.6  4832.9
  4869.5  4872.7  4878.1    4922  4953.3  4987.6  4994.6  4997.6  4998.8  4999.9
  5001.1  5001.3  5002.1  5005.1  5005.5  5009.1  5049.8  5052.5  5096.2  5097.8
  5142.8  5144.5  5188.9  5189.2  5230.7  5259.2  5274.7  5300.7  5690.7  5770.7
  5780.7  5820.7  5850.7  5930.7  5940.7  5951.8  6015.1
   144.3     144   144.4   143.6   141.5  141.79   141.9   141.6   142.5   141.6
   141.2   142.2   142.2   141.3   140.8   141.2     141  139.67  139.59  139.57
   139.5  139.33  139.34  139.41  139.46  139.51  139.52  139.53  139.53  139.53
  139.53  139.53  139.54  139.54  139.54   139.5  139.14  139.12  138.78  138.77
  138.68  138.68   138.7   138.7  138.46  139.14  139.54   140.2   141.4   142.1
   142.5   142.3   142.9   143.7   144.4  144.53   145.3
                                                                                
                                                                                
                                                                                
                                                                                
                                                                                
                                                        
  3334.4  3474.4  3504.4  3574.4  3844.4  3954.4  3994.4  4104.4  4164.4  4244.4
  4304.4  4334.4  4344.4  4364.4  4394.4  4624.4  4754.4  4819.2  4823.6  4832.9
  4869.5  4872.7  4878.1    4922  4953.3  4987.6  4994.6  4997.6  4998.8  4999.9
  5001.1  5001.3  5002.1  5005.1  5005.5  5009.1  5049.8  5052.5  5096.2  5097.8
  5142.8  5144.5  5188.9  5189.2  5230.7  5259.2  5274.7  5300.7  5690.7  5770.7
  5780.7  5820.7  5850.7  5930.7  5940.7  5951.8  6015.1
  144.79  144.49  144.89  144.09  141.99  142.28  142.39  142.09  142.99  142.09
  141.69  142.69  142.69  141.79  141.29  141.69  141.49  140.15  140.06  139.57
   139.5  139.33  139.34  139.41  139.46  139.51  139.52  139.53  139.53  139.53
  139.53  139.53  139.54  139.54  139.54   139.5  139.14  139.12  138.78  138.77
  138.69  138.69  138.73  138.73  138.89  139.62  140.02  140.69  141.89  142.59
  142.99  142.79  143.39  144.19  144.89  145.02  145.79
                                                                                
                                                                                
                                                                                
                                                                                
                                                                                
                                                        
BR Coef= 1 , 0 , 0 ,1.25, 0 ,,,.8,0,2,0,
WSPro=,,,, 1 ,,,, 0 ,,,, 0 ,,,,-1 ,-1 ,-1 , 0 , 0 , 0 , 0 , 0
Culvert=1,5,,32,.015,.2,1,1,3,133.21,4999.8,133.5,4999.8,Culvert #1  , 0 ,10
Culvert Bottom n=.015
BC Design=,, 0 ,, 0 ,,,,,,

Type RM Length L Ch R = 1 ,19525.8 ,110.6,57.8,44.6
BEGIN DESCRIPTION:
Downstream Section of Bridge/Culvert/Weir
END DESCRIPTION:
XS GIS Cut Line= 6
      3061087.83     13944348.43      3060377.51      13943912.4
      3060400.85     13943877.63      3060425.47     13943816.54
      3060400.74     13943616.58 3060266.550233613943031.8230589
#Sta/Elev= 30
  4103.9  144.41  4143.9  143.89  4153.9  144.36  4183.9  144.43  4243.9  143.33
  4263.9  144.12  4313.9  143.34  4383.9  143.76  4473.9  142.59  4773.9  140.93
  4793.9  141.13  4823.6  140.06  4832.9  138.92  4878.1  138.24    4922  138.38
  4987.6  138.44  4994.6  137.76  4999.9  133.71  5001.1  133.96  5001.3   134.8
  5005.5  137.29  5009.1  138.07  5049.8  138.38  5188.9  138.24  5246.6  140.06
  5476.6  140.76  5596.6  142.82  5806.6  143.93  5826.6  143.71  5846.6  144.51
#Mann= 5 ,-1 , 0
  4103.9     .08       0    4922      .1       0  4987.6     .06       0
  5476.6      .1       0  5596.6     .08       0
#XS Ineff= 2 , 0
       0 4997.31   138.5  5002.3       0  138.07
Permanent Ineff=
       F       F
Bank Sta=4987.6,5009.1
XS Rating Curve= 0
Exp/Cntr=.5,.3

Type RM Length L Ch R = 1 ,19468.  ,843,841,749.5
BEGIN DESCRIPTION:
VALKA_DS - XS 1
END DESCRIPTION:
XS GIS Cut Line= 4
       3061151.1      13944285.1      3060485.48     13943873.07
      3060435.94     13943810.61      3060335.96      13943016.9
#Sta/Elev= 30
  4163.2  144.98  4183.2  144.76  4193.2  144.17  4533.2  142.82  4663.2  141.82
  4693.2  142.09  4753.2  140.77    4922  139.99  4956.1  140.04 4986.93  138.37
 4994.35  137.58 4999.97  133.63 5001.42  133.95 5001.66  134.76 5002.62  135.38
 5006.71  137.28 5011.05  138.08  5025.8  138.57  5075.8  138.02  5125.8  138.71
  5135.8  138.24  5165.8  138.47  5205.8  139.81  5415.8  140.15  5465.8  141.63
  5555.8  143.21    5600   143.2  5795.8  143.15  5815.8  144.31  5825.8  144.41
#Mann= 5 ,-1 , 0
  4163.2     .08       0    4922      .1       0 4994.35     .06       0
  5465.8      .1       0    5600     .08       0
Bank Sta=4994.35,5011.05
XS Rating Curve= 0
Exp/Cntr=.3,.1

Type RM Length L Ch R = 1 ,18627.  ,90.5,63.9,63.5
BEGIN DESCRIPTION:
SHIMMERING PINES_US - XS 4
END DESCRIPTION:
XS GIS Cut Line= 3
      3061968.23       13944222.      3061059.08     13943281.61
      3060578.32     13942922.98
#Sta/Elev= 30
  3499.3  142.41  3529.3  142.07  3589.3   142.7  3619.3  141.87  3819.3   142.7
  3829.3  142.03  3869.3  141.41  3919.3  141.19  3989.3  142.07  4119.3   142.5
  4129.3  142.07  4349.3   141.2  4399.3  140.38  4439.3  140.65  4669.3  137.89
  4789.3   138.3  4877.6  137.66  4907.6   138.1 4977.24  137.28 4993.87  134.37
 5001.02   132.5 5006.05  133.79  5017.6  138.53  5107.6  138.75  5127.6  139.26
  5187.6  141.33  5217.6  143.84  5227.6  144.01  5277.6  142.52  5407.3  143.78
#Mann= 3 ,-1 , 0
  3499.3     .08       0 4977.24     .08       0  5017.6     .12       0
Bank Sta=4977.24,5017.6
XS Rating Curve= 0
Exp/Cntr=.5,.3

Type RM Length L Ch R = 1 ,18563.1 ,61,60,37.3
BEGIN DESCRIPTION:
Upstream Section of Bridge/Culvert/Weir
END DESCRIPTION:
XS GIS Cut Line= 4
      3062035.27     13944147.86      3061126.12     13943207.12
      3060846.79     13943050.97      3060588.55     13942865.27
#Sta/Elev= 30
  3495.5  142.26  3515.5  141.76  3535.5  142.36  3555.5  141.56  3575.5  142.66
  3955.5  140.66  4215.5  141.06  4235.5  140.36  4365.5  140.36  4435.5  138.96
  4455.5  139.56  4745.5  137.66  4775.5  136.76  4785.5  137.26  4795.5  136.56
  4801.7  137.73  4976.5   137.2  5001.1  132.41  5011.9  136.06  5041.5  138.27
  5122.8  138.47  5123.8  139.16  5163.8  140.96  5193.8  141.06  5223.8  142.46
  5253.8  141.96  5273.8  143.16  5343.8  143.56  5383.8  142.46  5441.9  144.46
#Mann= 3 ,-1 , 0
  3495.5     .08       0  4976.5     .08       0  5041.5     .12       0
#XS Ineff= 2 , 0
       0 4991.68  137.72  5005.2       0  138.17
Permanent Ineff=
       F       F
Bank Sta=4976.5,5041.5
XS Rating Curve= 0
Exp/Cntr=.5,.3