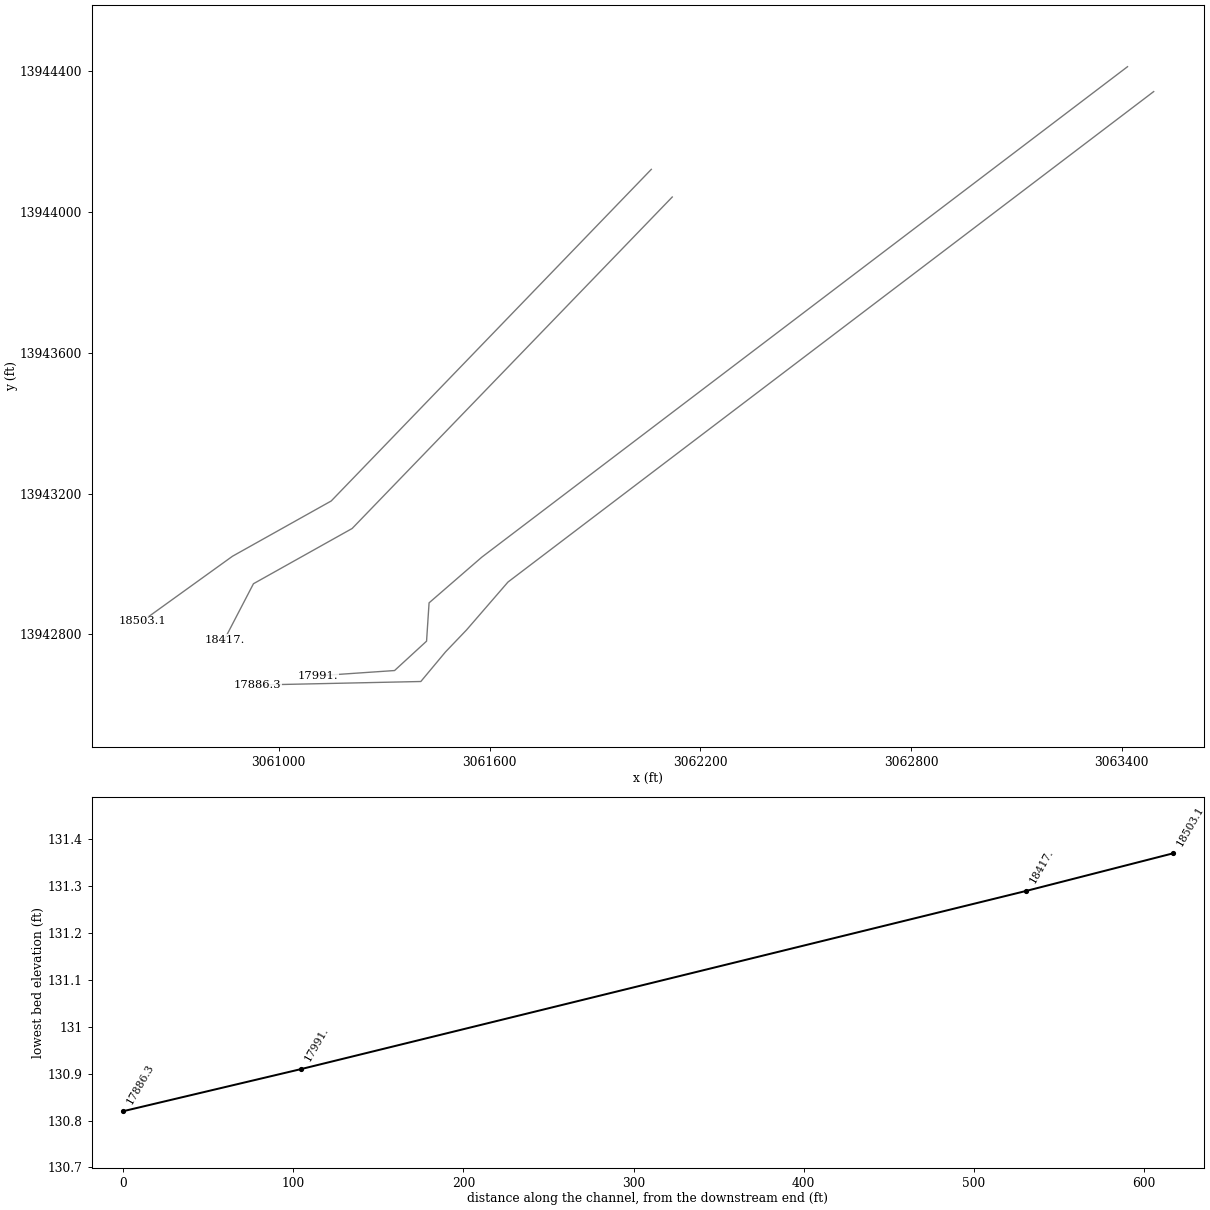
HEC-RAS study K131-02-00.prj: K131-02-00

--- K131-02-00.g01 (geometry) --- (continued)

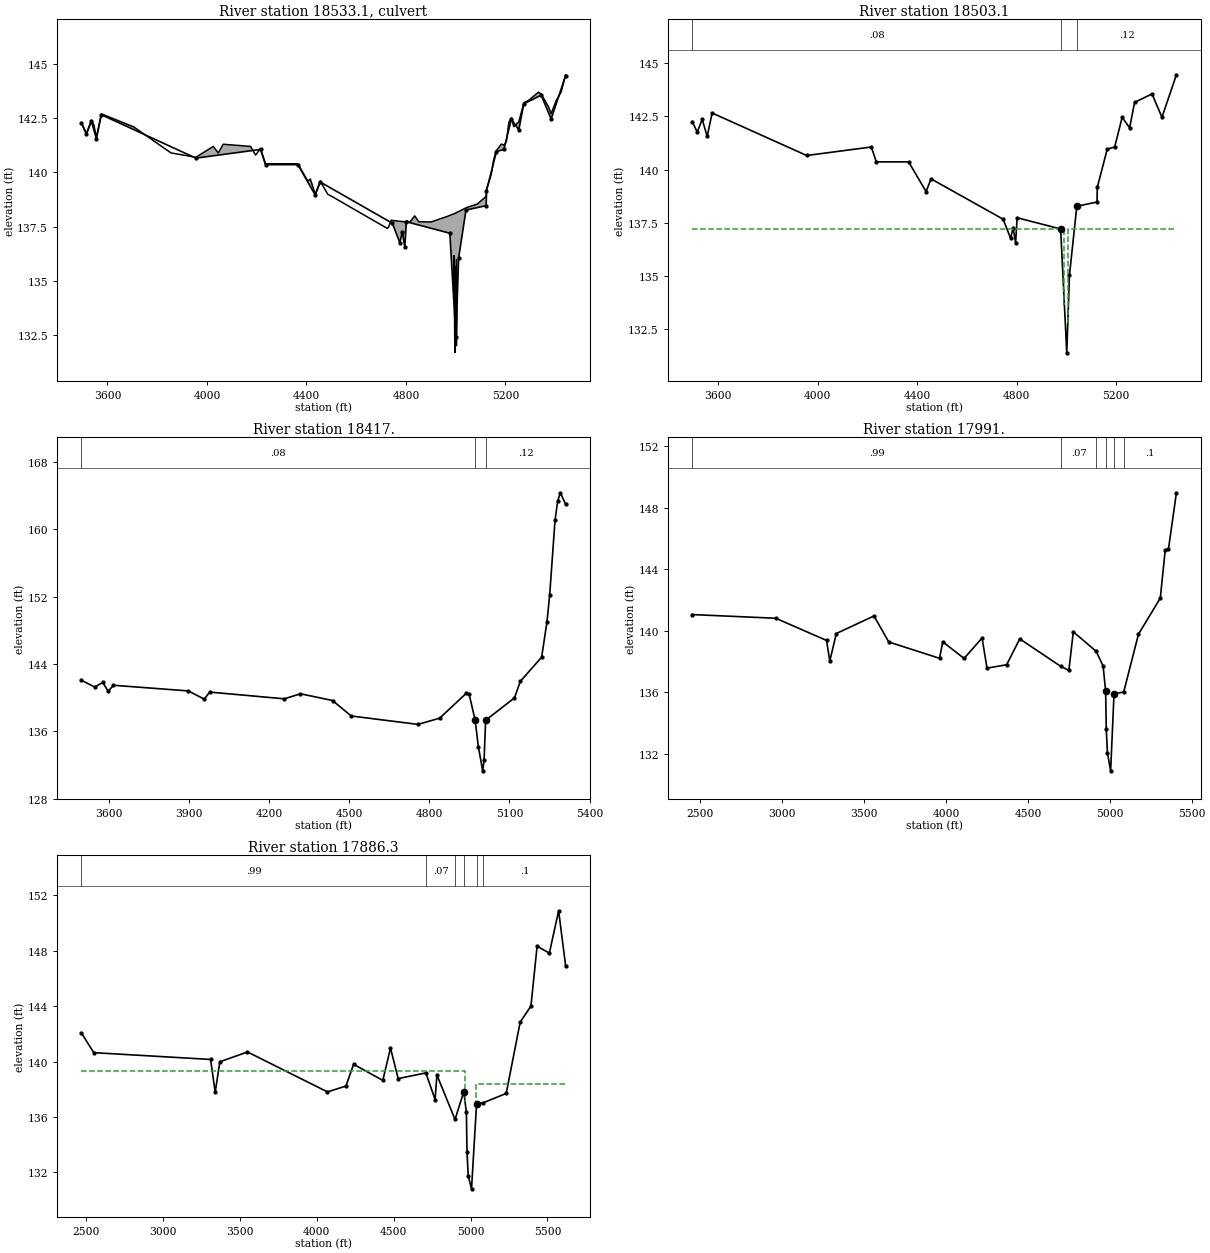
Type RM Length L Ch R = 2 ,18533.1 ,,,
BEGIN DESCRIPTION:
SHIMMERING PINES; Culvert slope inverted based on survey VRR
Structure ID: K131-02-00-S13
END DESCRIPTION:
Bridge Culvert--1,0,-1,-1, 0
Deck Dist Width WeirC Skew NumUp NumDn MinLoCord MaxHiCord MaxSubmerge Is_Ogee
10,40,2.6,0, 81, 81, , , .95, 0, ,,,
  3495.5  3515.5  3535.5  3545.5  3555.5  3575.5  3705.5  3855.5  3955.5  4025.5
  4045.5  4065.5  4175.5  4195.5  4215.5  4235.5  4365.5  4405.5  4415.5  4435.5
  4455.5  4485.5  4510.6  4725.5  4730.6  4740.6  4745.5  4775.5  4785.5  4795.5
  4801.5  4801.7  4815.3  4835.3  4851.7  4851.8  4901.1  4901.2  4949.6  4950.5
  4976.5  4986.8  4993.7  4996.7  5000.8  5001.1  5006.4  5011.9  5041.5  5045.8
    5086  5089.5  5118.4  5122.8    5123  5123.8    5143    5153  5153.8    5163
  5163.8  5183.8  5193.8  5203.8  5213.8  5223.8    5233  5233.8  5253.8    5273
  5273.8    5293    5333  5343.8    5373  5373.8  5383.8  5403.4  5403.8  5423.8
  5441.9
   142.3   141.8   142.4   142.2   141.6   142.7   142.1   140.9   140.7   141.2
   140.9   141.3   141.2   140.8   141.1   140.4   140.4   139.6   139.7     139
   139.6     139  138.84  137.42  137.49   137.8  137.79  137.75  137.74  137.73
  137.72  137.78   137.7     138  137.73  137.73  137.72  137.72  137.91  137.91
  138.02  138.07   138.1  138.11  138.13  138.14  138.17   138.2  138.37  138.39
  138.54  138.57  138.86   138.9   138.9  139.21  139.91   140.6  140.63     141
  141.01  141.31  141.26  141.41  142.31  142.51  142.14  142.11  142.33  143.16
  143.21  143.32   143.7  143.61  143.03  143.01  142.71  143.29   143.3   143.7
   144.5
                                                                                
                                                                                
                                                                                
                                                                                
                                                                                
                                                                                
                                                                                
                                                                                
        
  3495.5  3515.5  3535.5  3545.5  3555.5  3575.5  3705.5  3855.5  3955.5  4025.5
  4045.5  4065.5  4175.5  4195.5  4215.5  4235.5  4365.5  4405.5  4415.5  4435.5
  4455.5  4485.5  4510.6  4725.5  4730.6  4740.6  4745.5  4775.5  4785.5  4795.5
  4801.5  4801.7  4815.3  4835.3  4851.7  4851.8  4901.1  4901.2  4949.6  4950.5
  4976.5  4986.8  4993.7  4996.7  5000.8  5001.1  5006.4  5011.9  5041.5  5045.8
    5086  5089.5  5118.4  5122.8    5123  5123.8    5143    5153  5153.8    5163
  5163.8  5183.8  5193.8  5203.8  5213.8  5223.8    5233  5233.8  5253.8    5273
  5273.8    5293    5333  5343.8    5373  5373.8  5383.8  5403.4  5403.8  5423.8
  5441.9
   142.3   141.8   142.4   142.2   141.6   142.7   142.1   140.9   140.7   141.2
   140.9   141.3   141.2   140.8   141.1   140.4   140.4   139.6   139.7     139
   139.6     139  138.84  137.42  137.49   137.8  137.79  137.75  137.74  137.73
  137.72  137.78   137.7     138  137.73  137.73  137.72  137.72  137.91  137.91
  138.02  138.07   138.1  138.11  138.13  138.14  138.17   138.2  138.37  138.39
  138.54  138.57  138.86   138.9   138.9  139.21  139.91   140.6  140.63     141
  141.01  141.31  141.26  141.41  142.31  142.51  142.14  142.11  142.33  143.16
  143.21  143.32   143.7  143.61  143.03  143.01  142.71  143.29   143.3   143.7
   144.5
                                                                                
                                                                                
                                                                                
                                                                                
                                                                                
                                                                                
                                                                                
                                                                                
        
BR Coef= 1 , 0 , 0 ,1.25, 0 ,,,.8,0,2,0,
WSPro=,,,, 1 ,,,, 0 ,,,, 0 ,,,,-1 ,-1 ,-1 , 0 , 0 , 0 , 0 , 0
Culvert=1,2,,40,.024,.9,1,2,3,134.19,4992.7,133.64,4992.7,Culvert #1  , 0 ,10
Culvert Bottom n=.024
Culvert=1,4,,40,.024,.9,1,2,3,131.69,4997.3,131.88,4997.3,Culvert #2  , 0 ,10
Culvert Bottom n=.024
Culvert=1,4,,40,.024,.9,1,2,3,132,5003.2,132.06,5003.2,Culvert #3  , 0 ,10
Culvert Bottom n=.024
BC Design=,, 0 ,, 0 ,,,,,,

Type RM Length L Ch R = 1 ,18503.1 ,105.4,86.1,85
BEGIN DESCRIPTION:
Downstream Section of Bridge/Culvert/Weir
END DESCRIPTION:
XS GIS Cut Line= 4
      3062060.56     13944121.63      3061149.37     13943178.76
      3060868.45     13943021.73      3060611.14      13942836.7
#Sta/Elev= 30
  3495.5  142.26  3515.5  141.76  3535.5  142.36  3555.5  141.56  3575.5  142.66
  3955.5  140.66  4215.5  141.06  4235.5  140.36  4365.5  140.36  4435.5  138.96
  4455.5  139.56  4745.5  137.66  4775.5  136.76  4785.5  137.26  4795.5  136.56
  4801.7  137.73  4976.5   137.2  5001.1  131.37  5011.9  135.02  5041.5  138.27
  5122.8  138.47  5123.8  139.16  5163.8  140.96  5193.8  141.06  5223.8  142.46
  5253.8  141.96  5273.8  143.16  5343.8  143.56  5383.8  142.46  5441.9  144.46
#Mann= 3 ,-1 , 0
  3495.5     .08       0  4976.5     .06       0  5041.5     .12       0
#XS Ineff= 2 , 0
       0 4991.68   137.2  5005.2       0   137.2
Permanent Ineff=
       F       F
Bank Sta=4976.5,5041.5
XS Rating Curve= 0
Exp/Cntr=.5,.3

Type RM Length L Ch R = 1 ,18417.  ,351.5,426,491.2
BEGIN DESCRIPTION:
SHIMMERING PINES_DS - XS 1
END DESCRIPTION:
XS GIS Cut Line= 4
      3062120.16       13944043.      3061208.96     13943100.55
      3060928.05     13942943.52      3060845.15     13942784.23
#Sta/Elev= 30
  3497.5  142.05  3547.5  141.25  3577.5   141.8  3597.5  140.74  3617.5  141.46
  3897.5  140.79  3957.5  139.81  3977.5  140.65  4257.5  139.85  4317.5  140.45
  4437.5  139.65  4507.5  137.81  4757.5  136.81  4838.7  137.55  4938.7  140.52
  4948.7  140.44  4971.6  137.29  4983.4  134.18  4999.8  131.29 5004.96  132.56
  5010.7   137.3  5118.7  139.96  5140.5  141.92  5220.5   144.8  5240.5  149.04
  5250.5  152.18  5270.5  161.05  5280.5  163.37  5290.5  164.34  5310.1  162.97
#Mann= 3 ,-1 , 0
  3497.5     .08       0  4971.6     .06       0  5010.7     .12       0
Bank Sta=4971.6,5010.7
XS Rating Curve= 0
Exp/Cntr=.3,.1

Type RM Length L Ch R = 1 ,17991.  ,123.6,104.7,63
BEGIN DESCRIPTION:
SPRING CYPRESS_US - XS 4
END DESCRIPTION:
XS GIS Cut Line= 6
      3063416.12      13944413.5      3061578.11      13943019.1
      3061427.95     13942889.15      3061420.81     13942780.21
      3061329.72     13942696.71      3061111.98     13942681.77
#Sta/Elev= 30
  2450.2  141.06  2960.2  140.82  3270.2  139.38  3290.2  138.05  3330.2  139.83
  3560.2  140.97  3650.2  139.28  3960.2  138.22  3980.2  139.29  4110.2  138.21
  4220.2  139.54  4250.2  137.58  4370.2   137.8  4450.2  139.48  4700.2   137.7
  4750.2  137.43  4777.3  139.94  4917.3  138.67 4959.23  137.72 4974.75  136.08
 4978.49  133.62  4985.7  132.08 5005.25  130.91  5025.9  135.91  5085.1  136.03
  5175.1  139.78  5308.6  142.13  5338.6  145.25  5358.6  145.33  5406.9  148.97
#Mann= 6 ,-1 , 0
  2450.2     .99       0  4700.2     .07       0  4917.3     .06       0
 4974.75      .1       0  5025.9     .06       0  5085.1      .1       0
Bank Sta=4974.75,5025.9
XS Rating Curve= 0
Exp/Cntr=.5,.3

Type RM Length L Ch R = 1 ,17886.3 ,93,95,102.3
BEGIN DESCRIPTION:
Upstream Section of Bridge/Culvert/Weir
END DESCRIPTION:
XS GIS Cut Line= 6
      3063490.61     13944342.75       3061652.6     13942948.34
      3061534.62     13942812.14      3061474.76     13942749.68
       3061404.5     13942665.54      3060939.25     13942655.56
#Sta/Elev= 30
  2469.1  142.06  2549.1  140.64  3309.1  140.15  3339.1  137.78  3369.1  139.98
  3549.1  140.69  4069.1  137.81  4189.1  138.23  4239.1   139.8  4429.1  138.64
  4479.1  140.97  4529.1  138.77  4709.1  139.18  4769.1  137.26    4781  139.03
  4898.8  135.82  4955.7  137.83  4972.7  136.33  4976.8  133.47  4984.7  131.75
  5006.1  130.82    5039  136.97  5083.2  137.03  5231.7   137.7  5322.5  142.84
  5392.5     144  5432.5  148.31  5512.5  147.82  5572.5  150.87  5617.9  146.92
#Mann= 6 ,-1 , 0
  2469.1     .99       0  4709.1     .07       0  4898.8     .06       0
  4955.7      .1       0    5039     .06       0  5083.2      .1       0
#XS Ineff= 2 , 0
       0 4964.47   139.3 5038.15       0   138.4
Permanent Ineff=
       F       F
Bank Sta=4955.7,5039
XS Rating Curve= 0
Exp/Cntr=.5,.3