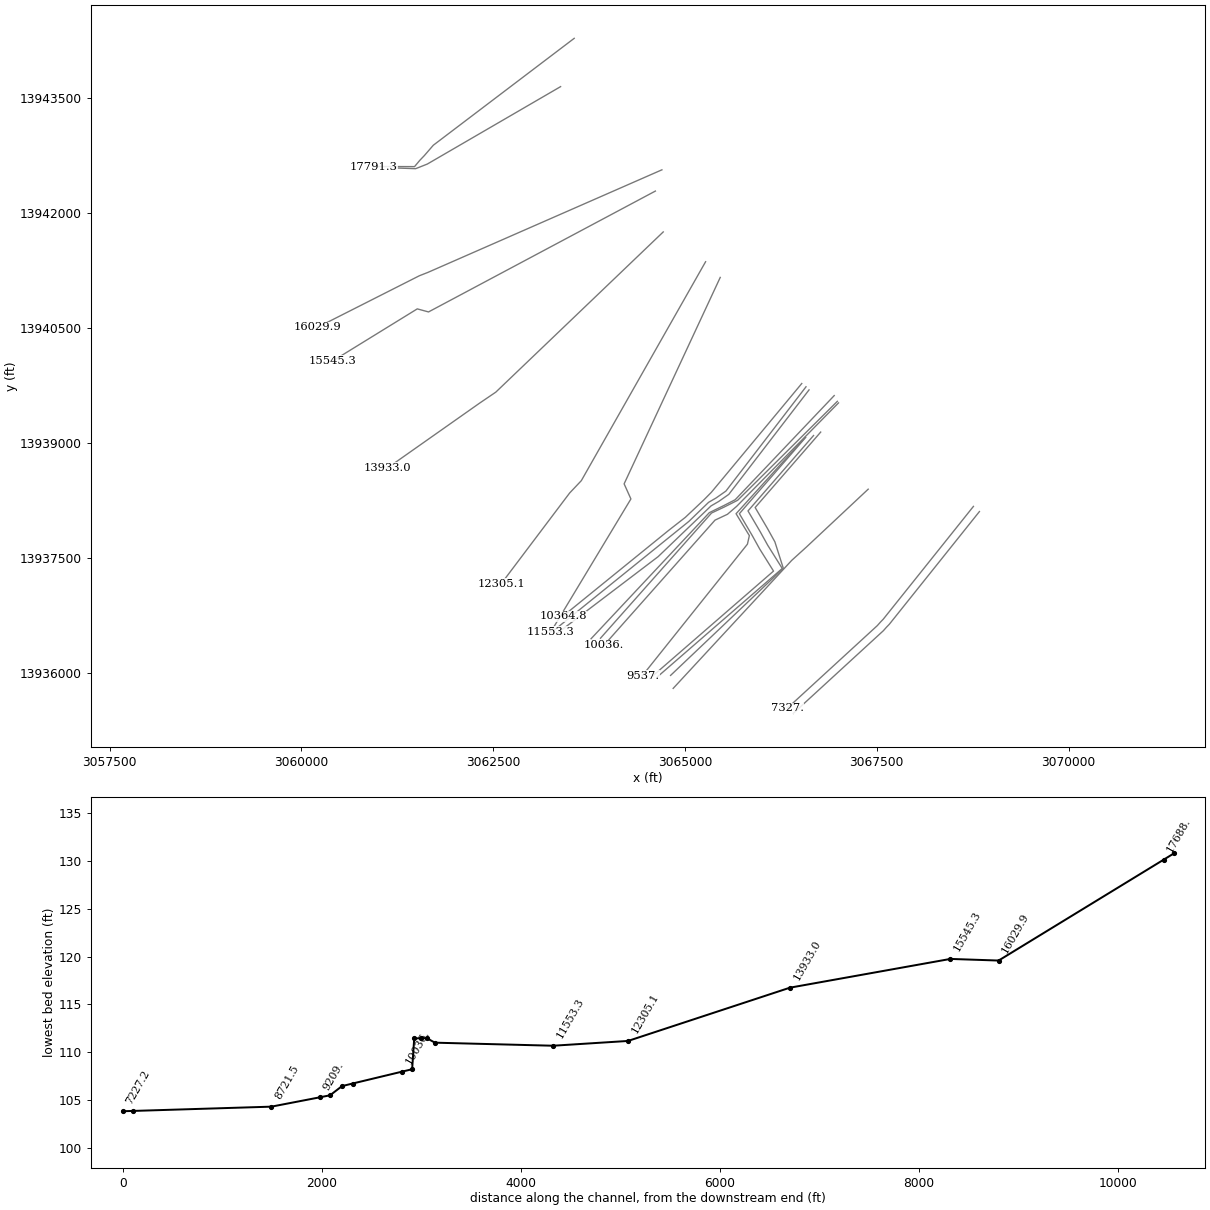
HEC-RAS study K131-02-00.prj: K131-02-00

--- K131-02-00.g01 (geometry) --- (continued)

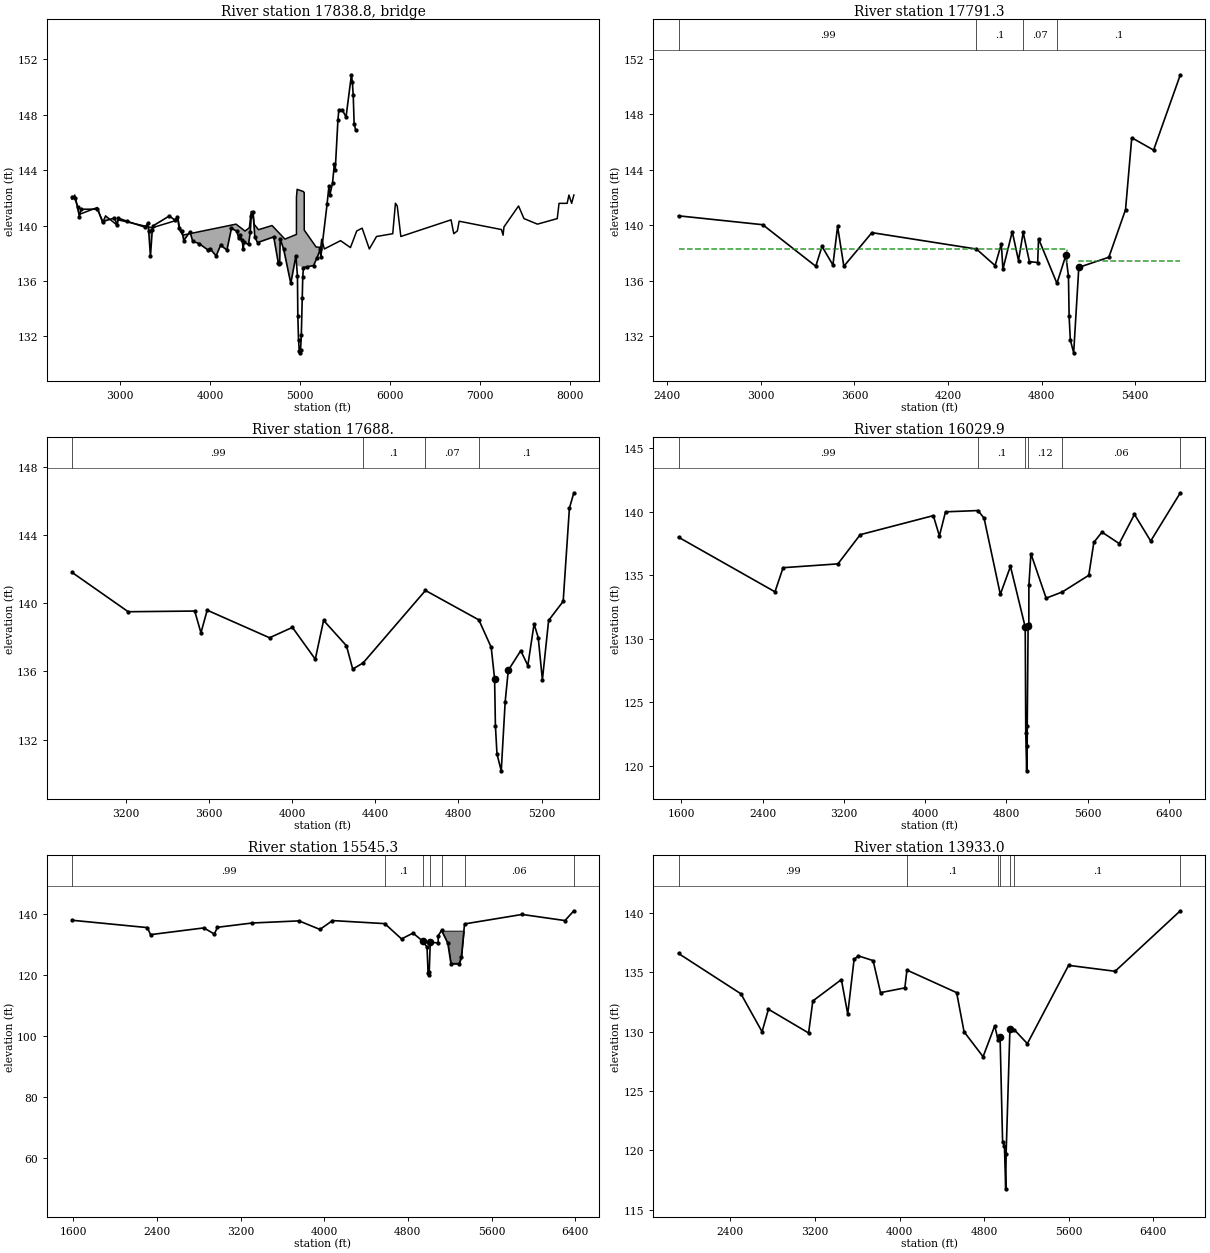
Type RM Length L Ch R = 3 ,17838.8 ,,,
BEGIN DESCRIPTION:
SPRING CYPRESS
Structure ID: K131-02-00-S12
END DESCRIPTION:
Bridge Culvert--1,0,-1,-1, 0
Deck Dist Width WeirC Skew NumUp NumDn MinLoCord MaxHiCord MaxSubmerge Is_Ogee
10,75,2.6,0, 60, 60, , , .95, 0, ,,,
  2468.1  2498.1  2548.1  2748.1  2808.1    2840  2968.1  2978.1  3358.1  3648.1
  3668.1  3698.1    4290    4390  4438.1  4458.1  4478.1    4490    4540    4690
  4833.6 4961.39  4961.5 4964.23  4964.3    4969    5039 5047.89    5048 5048.11
  5180.2  5231.7  5241.5  5271.5  5451.5  5561.5  5631.5  5691.5  5771.5  5851.5
  6031.5  6061.5  6081.5  6121.5  6679.6  6709.6  6749.6  6769.6  7239.6  7257.6
  7267.6  7429.6  7489.6  7639.6  7859.6  7879.6  7969.6  7989.6  8019.6  8044.2
   141.9   142.2   140.8   141.3   140.2   140.7  140.03  140.41  139.84  140.41
  139.61  139.31   140.1   139.6  139.84  141.01  141.01   140.1   139.7     140
  139.02  139.36  142.06  142.25  142.26  142.61  142.45  142.37  142.37  139.67
  138.45  138.43  139.01  138.31  138.91  138.41  139.61  139.81  138.31  139.21
  139.41  141.61  141.41  139.21  140.41  139.41  139.61  140.31  139.71   139.3
   139.9  141.41   140.5   140.1   140.5   141.6   141.6   142.2   141.6   142.2
                                                                                
                                                                                
                                  137.07  137.11  136.97
                                                                                
                                                                                
                                                                                
  2468.1  2498.1  2548.1  2748.1  2808.1    2840  2968.1  2978.1  3358.1  3648.1
  3668.1  3698.1    4290    4390  4438.1  4458.1  4478.1    4490    4540    4690
  4833.6 4961.39  4961.5 4964.23  4964.3    4969    5039 5047.89    5048 5048.11
  5180.2  5231.7  5241.5  5271.5  5451.5  5561.5  5631.5  5691.5  5771.5  5851.5
  6031.5  6061.5  6081.5  6121.5  6679.6  6709.6  6749.6  6769.6  7239.6  7257.6
  7267.6  7429.6  7489.6  7639.6  7859.6  7879.6  7969.6  7989.6  8019.6  8044.2
   141.9   142.2   140.8   141.3   140.2   140.7  140.03  140.41  139.84  140.41
  139.61  139.31   140.1   139.6  139.84  141.01  141.01   140.1   139.7     140
  139.02  139.36  142.06  142.25  142.26  142.61  142.45  142.37  142.37  139.67
  138.45  138.43  139.01  138.31  138.91  138.41  139.61  139.81  138.31  139.21
  139.41  141.61  141.41  139.21  140.41  139.41  139.61  140.31  139.71   139.3
   139.9  141.41   140.5   140.1   140.5   141.6   141.6   142.2   141.6   142.2
                                                                                
                                                                                
                                  137.07  137.11  136.97
                                                                                
                                                                                
                                                                                
BR Coef= 1 , 1 , 0 ,1.25, 0 ,,,.8,0,2,0,
WSPro=,,,, 1 ,,,, 0 ,,,, 0 ,,,,-1 ,-1 ,-1 , 0 , 0 , 0 , 0 , 0
BR U #Sta/Elev= 82
  2469.1  142.06  2499.1  142.01  2529.1  141.34  2549.1  140.64  2569.1  141.17
  2749.1  141.18  2809.1  140.29  2939.1  140.54  2969.1  140.03  2979.1  140.54
  3079.1  140.31  3279.1  139.88  3309.1  140.15  3319.1  139.64  3339.1  137.78
  3359.1  139.66  3369.1  139.98  3549.1  140.69  3609.1   140.4  3639.1  140.58
  3659.1  139.79  3689.1  139.62  3709.1  138.92  3779.1  139.54  3809.1  138.86
  3879.1   138.7  3979.1  138.23  3999.1  138.34  4069.1  137.81  4119.1  138.58
  4189.1  138.23  4239.1   139.8  4299.1  139.59  4319.1  139.09  4329.1  139.35
  4359.1  138.93  4369.1  138.32  4379.1  138.78  4429.1  138.64  4449.1  139.56
  4459.1  140.69  4479.1  140.97  4499.1  139.16  4529.1  138.77  4709.1  139.18
  4759.1  137.33  4769.1  137.26  4775.3  137.32    4781  139.03  4819.3   138.3
  4898.8  135.82  4955.7  137.83  4972.7  136.33  4976.8  133.47  4984.7  131.75
    4993  130.95  5006.1  130.82    5007  131.03  5015.6  132.08  5025.7  134.74
  5031.7  136.31    5039  136.97  5083.2  137.03  5151.4  137.11  5189.9  137.67
  5227.8   138.3  5231.7   137.7  5302.5  141.58  5322.5  142.84  5332.5  142.21
  5362.5  143.06  5382.5  144.42  5392.5     144  5422.5  147.62  5432.5  148.31
  5472.5  148.32  5512.5  147.82  5572.5  150.87  5582.5  150.35  5592.5   149.4
  5602.5  147.35  5617.9  146.92
BR U #Mann= 6
  2469.1     .99  4709.1     .07  4898.8     .06  4955.7     .04    5039     .06
  5083.2      .1
BR D #Sta/Elev= 141
  2472.3  140.68  2522.3  141.17  2542.3  141.89  2562.3  141.14  2592.3  140.65
  2892.3  140.16  2902.3   139.9  2942.3  140.25  2982.3  139.79  3012.3  140.04
  3022.3  139.12  3032.3  139.68  3052.3  139.16  3152.3  138.85  3162.3   139.4
  3172.3  138.61  3192.3  139.09  3202.3  138.61  3262.3   138.9  3282.3     138
  3292.3  138.14  3312.3  137.63  3322.3  138.31  3342.3  137.16  3352.3  137.05
  3362.3  138.09  3392.3  138.48  3412.3  137.96  3422.3  138.42  3432.3  137.81
  3442.3  138.39  3452.3  137.55  3462.3  137.14  3482.3  139.88  3492.3  139.92
  3512.3  137.53  3532.3  137.05  3552.3  137.89  3562.3  137.57  3592.3  137.42
  3652.3  138.46  3662.3  138.14  3682.3  139.34  3712.3  139.47  3722.3  138.78
  3732.3  139.23  3752.3  139.15  3762.3  139.53  3772.3  138.79  3782.3  139.31
  3792.3  138.88  3832.3  139.39  3872.3  139.15  3882.3  139.36  3912.3  138.95
  4002.3  139.32  4022.3  138.82  4132.3  138.65  4152.3     139  4172.3  138.42
  4182.3   138.6  4192.3  138.04  4212.3  138.55  4222.3  137.71  4232.3  138.81
  4242.3   137.9  4252.3  138.38  4272.3  137.82  4282.3  138.45  4292.3  137.94
  4312.3  138.28  4352.3  137.51  4362.3  138.24  4372.3  137.46  4382.3  138.29
  4402.3  137.44  4412.3   138.3  4422.3  137.44  4432.3  138.07  4442.3  137.54
  4452.3  137.46  4462.3  137.84  4482.3  137.52  4492.3  137.98  4502.3   137.1
  4512.3   138.2  4522.3  137.71  4532.3  137.89  4542.3  138.67  4552.3  136.83
  4562.3  138.41  4572.3  137.51  4592.3  139.12  4612.3  139.54  4632.3  137.81
  4642.3  138.53  4652.3  137.46  4662.3  138.35  4672.3   138.6  4682.3  139.49
  4692.3  139.81  4702.3  138.71  4722.3  137.38  4732.3  137.75  4762.3  137.08
  4775.3  137.32    4781  139.03  4819.3   138.3  4898.8  135.82  4955.7  137.83
  4972.7  136.33  4976.8  133.47  4984.7  131.75    4993  130.95  5006.1  130.82
    5007  131.03  5015.6  132.08  5025.7  134.74  5031.7  136.31    5039  136.97
  5083.2  137.03  5151.4  137.11  5189.9  137.67  5227.8   138.3  5231.7   137.7
  5238.6  138.48  5248.6  139.19  5318.6  139.96  5338.6  141.12  5348.6  142.36
  5358.6  144.39  5378.6   146.3  5408.6  145.97  5418.6  146.37  5448.6     146
  5458.6  146.64  5488.6  145.48  5518.6  145.41  5628.6   149.1  5668.6  150.59
    5690  150.83
BR D #Mann= 6
  2472.3     .99  4382.3      .1  4682.3     .07  4898.8      .1  4955.7     .04
    5039      .1
BC Design=,, 0 ,, 0 ,,,,,,

Type RM Length L Ch R = 1 ,17791.3 ,130.1,103.3,55.7
BEGIN DESCRIPTION:
Downstream Section of Bridge/Culvert/Weir **See Note**
Confluence of K131-02-00 and K131-02-04 approximately 800' downstream of Spring-Cypress Road.
END DESCRIPTION:
XS GIS Cut Line= 6
      3063556.67     13944274.03      3061720.32     13942880.88
      3061603.38     13942745.88      3061543.65     13942683.55
      3061475.48     13942601.92      3060934.04     13942603.47
#Sta/Elev= 30
  2472.3  140.68  3012.3  140.04  3352.3  137.05  3392.3  138.48  3462.3  137.14
  3492.3  139.92  3532.3  137.05  3712.3  139.47  4382.3  138.29  4502.3   137.1
  4542.3  138.67  4552.3  136.83  4612.3  139.54  4652.3  137.46  4682.3  139.49
  4722.3  137.38  4775.3  137.32    4781  139.03  4898.8  135.82  4955.7  137.83
  4972.7  136.33  4976.8  133.47  4984.7  131.75  5006.1  130.82    5039  136.97
  5231.7   137.7  5338.6  141.12  5378.6   146.3  5518.6  145.41    5690  150.83
#Mann= 4 ,-1 , 0
  2472.3     .99       0  4382.3      .1       0  4682.3     .07       0
  4898.8      .1       0
#XS Ineff= 2 , 0
       0 4964.47   138.3 5038.15       0   137.4
Permanent Ineff=
       F       F
Bank Sta=4955.7,5039
XS Rating Curve= 0
Exp/Cntr=.5,.3

Type RM Length L Ch R = 1 ,17688.  ,1660,1658.1,1545.9
BEGIN DESCRIPTION:
SPRING CYPRESS_DS - XS 1
END DESCRIPTION:
XS GIS Cut Line= 4
      3063378.98      13943644.4      3061642.27     13942635.54
      3061489.81     13942575.04       3061248.6     13942583.57
#Sta/Elev= 30
  2941.2  141.82  3211.2  139.51  3531.2  139.55  3561.2  138.27  3591.2   139.6
  3891.2  137.98  4001.2  138.59  4111.2  136.72  4151.2     139  4261.2  137.51
  4291.2  136.14  4341.2   136.5  4641.2  140.76    4898  139.03 4957.48  137.42
 4973.77  135.58  4977.7  132.82 4985.26  131.15 5005.77  130.16 5024.71  134.22
  5039.7  136.07  5099.7  137.22  5133.7  136.35  5163.7  138.79  5183.7  137.99
  5203.7  135.51  5233.7     139  5303.7  140.12  5333.7   145.6  5355.1   146.5
#Mann= 4 ,-1 , 0
  2941.2     .99       0  4341.2      .1       0  4641.2     .07       0
    4898      .1       0
Bank Sta=4973.77,5039.7
XS Rating Curve= 0
Exp/Cntr=.3,.1

Type RM Length L Ch R = 1 ,16029.9 ,499.7,484.6,427.3
BEGIN DESCRIPTION:
Cross Section K131-02-00-X10
END DESCRIPTION:
XS GIS Cut Line= 4
      3064699.87     13942560.23      3061651.59     13941223.95
      3061537.08     13941178.84      3060206.03     13940504.99
#Sta/Elev= 30
  1570.8     138  2520.8   133.7  2600.8   135.6  3140.8   135.9  3360.8   138.2
  4080.8   139.7  4140.8   138.1  4200.8     140  4520.8   140.1  4580.8   139.5
  4740.8   133.5  4840.8   135.7  4986.1  130.92  4991.5  122.58  5000.4   119.6
  5005.6  121.54  5005.9  123.16  5014.6     131  5021.7  131.17  5022.2   134.2
  5042.2   136.7  5192.2   133.2  5351.9  133.69  5612.2     135  5662.2   137.6
  5742.2   138.4  5912.2   137.5  6062.2   139.8  6222.2   137.7  6514.1   141.5
#Mann= 6 ,-1 , 0
  1570.8     .99       0  4520.8      .1       0  4986.1      .1       0
  5014.6     .12       0  5351.9     .06       0  6514.1      .2       0
Bank Sta=4986.1,5014.6
XS Rating Curve= 0
Exp/Cntr=.3,.1

Type RM Length L Ch R = 1 ,15545.3 ,1461.2,1612.3,1618.3
BEGIN DESCRIPTION:
Cross Section K131-02-00-X09
END DESCRIPTION:
XS GIS Cut Line= 4
      3064614.68     13942283.36      3061657.66     13940707.79
      3061511.06      13940747.7      3060408.36     13940068.38
#Sta/Elev= 30
  1589.5   137.8  2309.5   135.4  2339.5   133.1  2849.5   135.3  2949.5   133.3
  2979.5   135.5  3309.5   136.9  3759.5   137.6  3959.5   134.8  4079.5   137.7
  4579.5   136.7  4739.5   131.7  4849.5   133.6  4941.4     131  4983.4  128.99
  4993.2  120.63  4999.5  119.77  5004.3  120.83  5014.3  130.56    5090  130.41
  5090.1   132.7    5122   134.5    5182   130.3    5212   123.6    5292   123.6
    5312   125.9    5342   136.6    5892   139.7    6302   137.7  6387.2   140.9
#Mann= 7 ,-1 , 0
  1589.5     .99       0  4579.5      .1       0  4941.4      .1       0
  5014.3      .1       0    5122    .026       0    5342     .06       0
  6387.2      .2       0
#Block Obstruct= 2 ,-1
 5122.65    5350   134.4    9000    9001      50
Bank Sta=4941.4,5014.3
XS Rating Curve= 0
Exp/Cntr=.3,.1

Type RM Length L Ch R = 1 ,13933.0 ,1610.8,1627.9,1639.5
BEGIN DESCRIPTION:
Cross Section K131-02-00-X8
END DESCRIPTION:
XS GIS Cut Line= 4
      3064717.12      13941750.7       3062534.7     13939662.46
       3062321.3     13939517.59      3061121.84     13938673.37
#Sta/Elev= 30
  1909.2   136.6  2499.2   133.2  2699.2     130  2759.2   131.9  3139.2   129.9
  3179.2   132.6  3449.2   134.4  3509.2   131.5  3569.2   136.1  3609.2   136.4
  3749.2     136  3819.2   133.3  4049.2   133.7  4069.2   135.2  4539.2   133.3
  4609.2     130  4789.2   127.9  4899.2   130.5    4931  129.31    4950  129.53
  4973.7  120.72  4991.2  120.37  5003.1  116.76  5006.9  119.68  5042.9  130.21
  5085.6  130.16  5207.7     129  5597.7   135.6  6037.7   135.1  6654.4   140.2
#Mann= 7 ,-1 , 0
  1909.2     .99       0  4069.2      .1       0    4931     .06       0
    4950     .04       0  5042.9     .06       0  5085.6      .1       0
  6654.4      .2       0
Bank Sta=4950,5042.9
XS Rating Curve= 0
Exp/Cntr=.3,.1

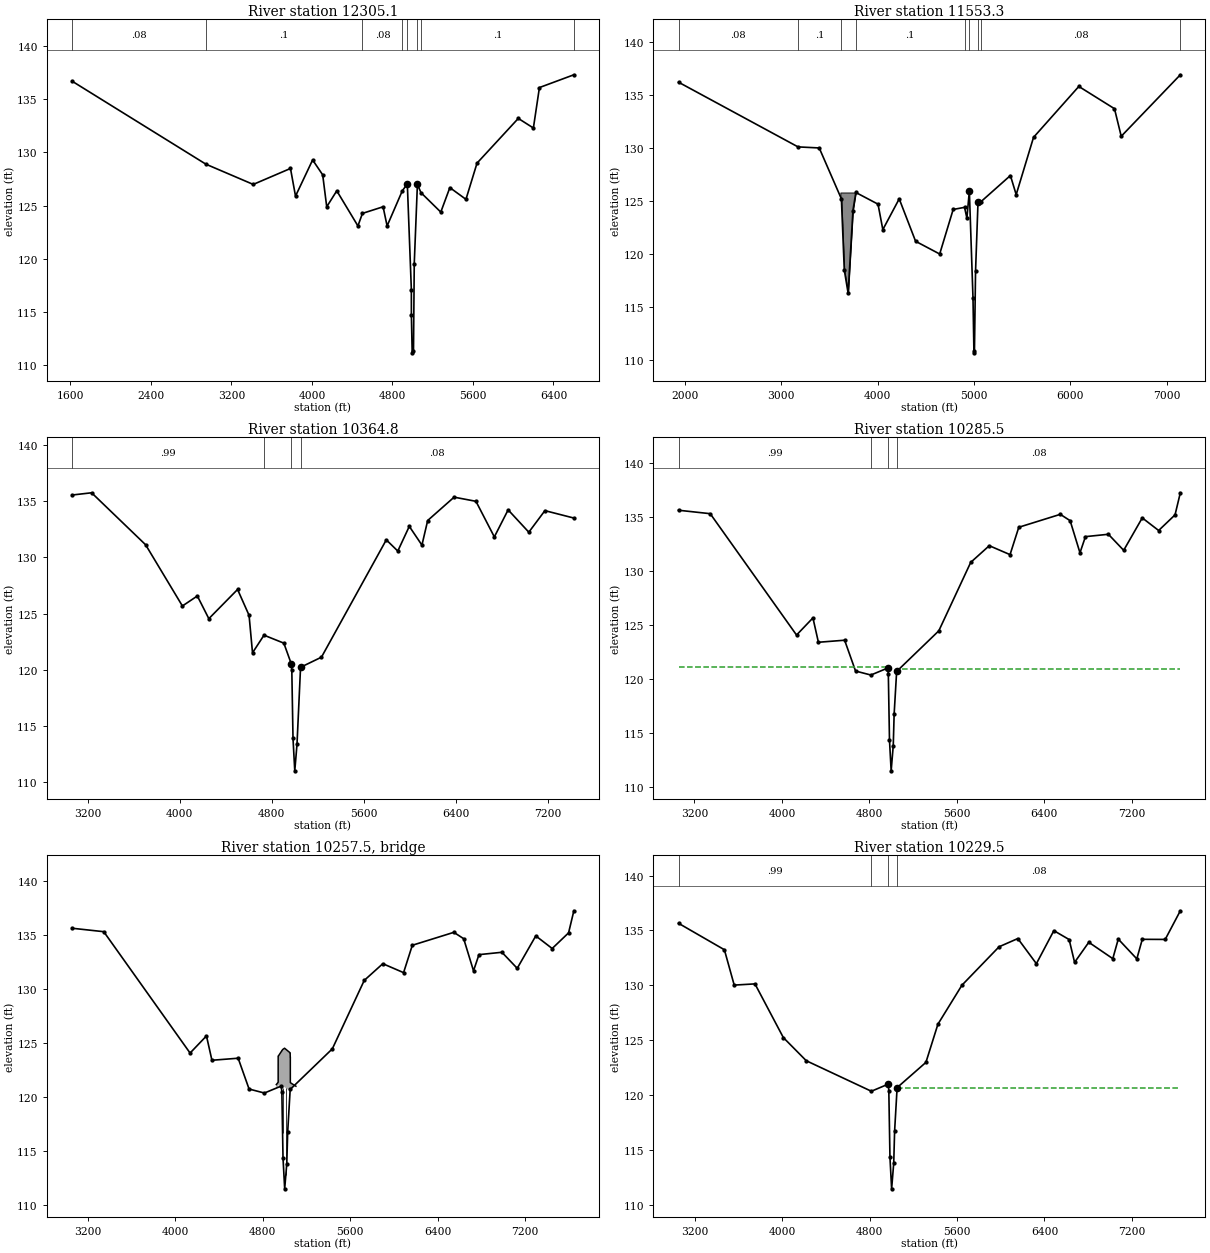
Type RM Length L Ch R = 1 ,12305.1 ,648.7,751.8,830.9
BEGIN DESCRIPTION:
Cross Section K131-02-00-X7
END DESCRIPTION:
XS GIS Cut Line= 4
      3065269.16     13941362.22      3063649.43      13938508.7
      3063496.75     13938347.35      3062604.38       13937164.
#Sta/Elev= 30
  1617.3   136.7  2947.3   128.9  3417.3     127  3787.3   128.5  3837.3   125.9
  4007.3   129.3  4107.3   127.9  4147.3   124.9  4247.3   126.4  4457.3   123.1
  4502.3  124.28  4707.3   124.9  4747.3   123.1  4898.3   126.4  4948.1  127.05
  4988.2  117.11  4988.5  114.72  4996.5  111.18  5009.4  111.35    5017  119.57
  5048.3  127.01  5083.4  126.23  5280.6   124.4  5370.6   126.7  5530.6   125.6
  5640.6     129  6050.6   133.2  6200.6   132.3  6260.6   136.1  6602.7   137.3
#Mann= 8 ,-1 , 0
  1617.3     .08       0  2947.3      .1       0  4502.3     .08       0
  4898.3     .06       0  4948.1     .04       0  5048.3     .06       0
  5083.4      .1       0  6602.7      .2       0
Bank Sta=4948.1,5048.3
XS Rating Curve= 0
Exp/Cntr=.3,.1

Type RM Length L Ch R = 1 ,11553.3 ,1276.2,1188.5,1070
BEGIN DESCRIPTION:
Cross Section K131-02-00-X6
END DESCRIPTION:
XS GIS Cut Line= 4
      3065459.99     13941157.77      3064207.22     13938467.06
      3064295.71     13938270.14      3063251.83     13936536.99
#Sta/Elev= 30
  1933.5   136.2  3173.5   130.1  3393.5     130  3623.5   125.2  3653.5   118.5
  3693.5   116.3  3743.5   124.1  3773.5   125.8  4003.5   124.7  4053.5   122.3
  4223.5   125.2  4393.5   121.2  4643.5     120  4783.5   124.2  4901.6   124.4
  4925.9  123.38  4951.4  125.95  4989.1  115.87    4999  110.68  5004.3  110.86
  5015.7  118.38  5041.2  124.89  5067.7   124.9  5377.4   127.4  5437.4   125.6
  5617.4     131  6087.4   135.8  6457.4   133.7  6527.4   131.1  7140.7   136.9
#Mann= 9 ,-1 , 0
  1933.5     .08       0  3173.5      .1       0  3623.5    .026       0
  3773.5      .1       0  4901.6     .06       0  4951.4     .04       0
  5041.2     .06       0  5067.7     .08       0  7140.7      .2       0
#XS Ineff= 2 , 0
       0                 5372.64       0  127.35
Permanent Ineff=
       F       F
#Block Obstruct= 1 ,-1
    3613    3773   125.8
Bank Sta=4951.4,5041.2
XS Rating Curve= 0
Exp/Cntr=.3,.1

Type RM Length L Ch R = 1 ,10364.8 ,96.5,79.3,67.1
BEGIN DESCRIPTION:
Cross Section K131-02-00-X5a-interp
END DESCRIPTION:
XS GIS Cut Line= 6
      3066522.59     13939774.88      3065344.98     13938357.67
      3065248.64       13938260.       3065004.6     13938029.98
      3064784.77     13937858.23      3063408.92      13936741.7
#Sta/Elev= 30
  3062.1  135.56  3232.1  135.76  3702.1  131.13  4022.1  125.68  4152.1  126.57
  4252.1  124.55  4502.1  127.15  4602.1  124.85  4632.1  121.51  4732.1  123.08
  4904.7  122.37    4969  120.54  4974.1  119.94  4984.5  113.88  4999.8     111
  5019.1  113.35  5050.1  120.22  5231.9  121.12  5796.2  131.57  5896.2  130.57
  5996.2  132.77  6106.2   131.1  6156.2  133.29  6386.2  135.37  6576.2     135
  6736.2  131.83  6856.2  134.24  7036.2  132.25  7176.2  134.17  7428.1  133.51
#Mann= 4 ,-1 , 0
  3062.1     .99       0  4732.1     .08       0    4969     .04       0
  5050.1     .08       0
Bank Sta=4969,5050.1
XS Rating Curve= 0
Exp/Cntr=.5,.3

Type RM Length L Ch R = 1 ,10285.5 ,57,56,55
BEGIN DESCRIPTION:
Upstream Section of Bridge/Culvert/Weir
END DESCRIPTION:
XS GIS Cut Line= 6
      3066578.11     13939732.24      3065534.15     13938372.99
      3065405.76     13938282.77       3065308.6     13938226.39
       3065050.6     13937977.08      3063299.95     13936563.13
#Sta/Elev= 30
    3054  135.64    3344  135.32    4134  124.06    4284  125.65    4334  123.39
    4574  123.58    4674  120.72  4814.3  120.35    4969     121  4974.1   120.4
  4984.5  114.34  4999.8  111.46  5019.1  113.81  5027.2  116.73  5050.1  120.68
  5435.9  124.45  5727.9   130.8  5897.9  132.35  6087.9  131.52  6167.9  134.06
  6547.9  135.26  6637.9  134.67  6727.9  131.69  6777.9  133.19  6987.9  133.41
  7127.9  131.92  7297.9  134.93  7447.9  133.76  7597.9  135.21  7646.3  137.26
#Mann= 4 ,-1 , 0
    3054     .99       0  4814.3     .08       0    4969     .04       0
  5050.1     .08       0
#XS Ineff= 2 , 0
       0 4971.91  121.13 5049.74       0  120.87
Permanent Ineff=
       F       F
Bank Sta=4969,5050.1
XS Rating Curve= 0
Exp/Cntr=.5,.3

Type RM Length L Ch R = 3 ,10257.5 ,,,
BEGIN DESCRIPTION:
THEISSWOOD Road
Structure ID: K131-02-00-S7-2
END DESCRIPTION:
Bridge Culvert--1,0,-1,-1, 0
Deck Dist Width WeirC Skew NumUp NumDn MinLoCord MaxHiCord MaxSubmerge Is_Ogee
10,36,2.6,0, 34, 34, , , .95, 0, ,,,
  4923.1 4940.09  4940.2 4940.31  4940.4    4969 4971.81 4971.93    4972    4974
  4977.6  4980.7  4984.5  4991.7  4994.3  4994.4  4998.7  4999.8  5005.6  5005.7
  5008.5  5010.4  5019.1  5027.2  5049.8  5049.9 5049.99  5050.1  5050.2  5050.6
 5051.39  5051.5 5051.61  5102.6
  121.13  121.35  123.75  123.75  123.76   124.2  124.24  124.25  124.25  124.28
  124.33  124.38  124.41  124.46  124.48  124.48  124.51   124.5  124.45  124.45
  124.43  124.41  124.34  124.27  124.08  124.08  124.08  124.08  124.01  123.72
  123.71  123.71  121.31  120.98
                                  121.08     121  120.66  120.65  120.65  120.68
  120.73  120.78  120.81  120.86  120.88  120.88  120.91   120.9  120.85  120.85
  120.83  120.81  120.74  120.67  120.66  120.68  120.68  120.68  120.68  120.68
                                
  4923.1 4940.09  4940.2 4940.31  4940.4    4969 4971.81 4971.93    4972    4974
  4977.6  4980.7  4984.5  4991.7  4994.3  4994.4  4998.7  4999.8  5005.6  5005.7
  5008.5  5010.4  5019.1  5027.2  5049.8  5049.9 5049.99  5050.1  5050.2  5050.6
 5051.39  5051.5 5051.61  5102.6
  121.13  121.35  123.75  123.75  123.76   124.2  124.24  124.25  124.25  124.28
  124.33  124.38  124.41  124.46  124.48  124.48  124.51   124.5  124.45  124.45
  124.43  124.41  124.34  124.27  124.08  124.08  124.08  124.08  124.01  123.72
  123.71  123.71  121.31  120.98
                                  121.08     121  120.66  120.65  120.65  120.68
  120.73  120.78  120.81  120.86  120.88  120.88  120.91   120.9  120.85  120.85
  120.83  120.81  120.74  120.67  120.66  120.68  120.68  120.68  120.68  120.68
                                
Pier Skew, UpSta & Num, DnSta & Num=  ,4980.6, 2 ,4980.6, 2 , 0 , 0 , 0 ,,
     1.4     1.4
  115.43  121.78
     1.4     1.4
  115.45   121.8
Pier Skew, UpSta & Num, DnSta & Num=  ,5010.4, 2 ,5010.4, 2 , 0 , 0 , 0 ,,
     1.4     1.4
  111.75  121.82
     1.4     1.4
  111.77  121.84
BR Coef= 1 , 1 , 1 ,1.25, 0 ,,,.8,0,2,0,
WSPro=,,,, 1 ,,,, 0 ,,,, 0 ,,,,-1 ,-1 ,-1 , 0 , 0 , 0 , 0 , 0
BC Design=,, 0 ,, 0 ,,,,,,

Type RM Length L Ch R = 1 ,10229.5 ,75.7,72.5,66.4
BEGIN DESCRIPTION:
Downstream Section of Bridge/Culvert/Weir
END DESCRIPTION:
XS GIS Cut Line= 6
      3066617.46     13939691.59      3065571.64     13938329.92
      3065440.04     13938237.44      3065339.99     13938179.38
      3064651.29     13937518.75      3063338.55     13936521.57
#Sta/Elev= 30
  3047.9  135.65  3467.9  133.24  3557.9  130.02  3747.9  130.13  4007.9  125.24
  4217.9  123.13  4814.3  120.35    4969     121  4974.1   120.4  4984.5  114.34
  4999.8  111.46  5019.1  113.81  5027.2  116.73  5050.1  120.68  5313.9  122.98
  5423.9  126.46  5643.9  130.01  5983.9  133.51  6155.8  134.26  6325.8  131.97
  6485.8  134.98  6625.8  134.17  6675.8  132.09  6805.8  133.92  7025.8  132.43
  7075.8  134.21  7245.8  132.41  7295.8  134.19  7505.8  134.18  7644.3  136.79
#Mann= 4 ,-1 , 0
  3047.9     .99       0  4814.3     .08       0    4969     .04       0
  5050.1     .08       0
#XS Ineff= 2 , 0
       0 4971.91  120.37 5049.74       0  120.68
Permanent Ineff=
       F       F
Bank Sta=4969,5050.1
XS Rating Curve= 0
Exp/Cntr=.5,.3

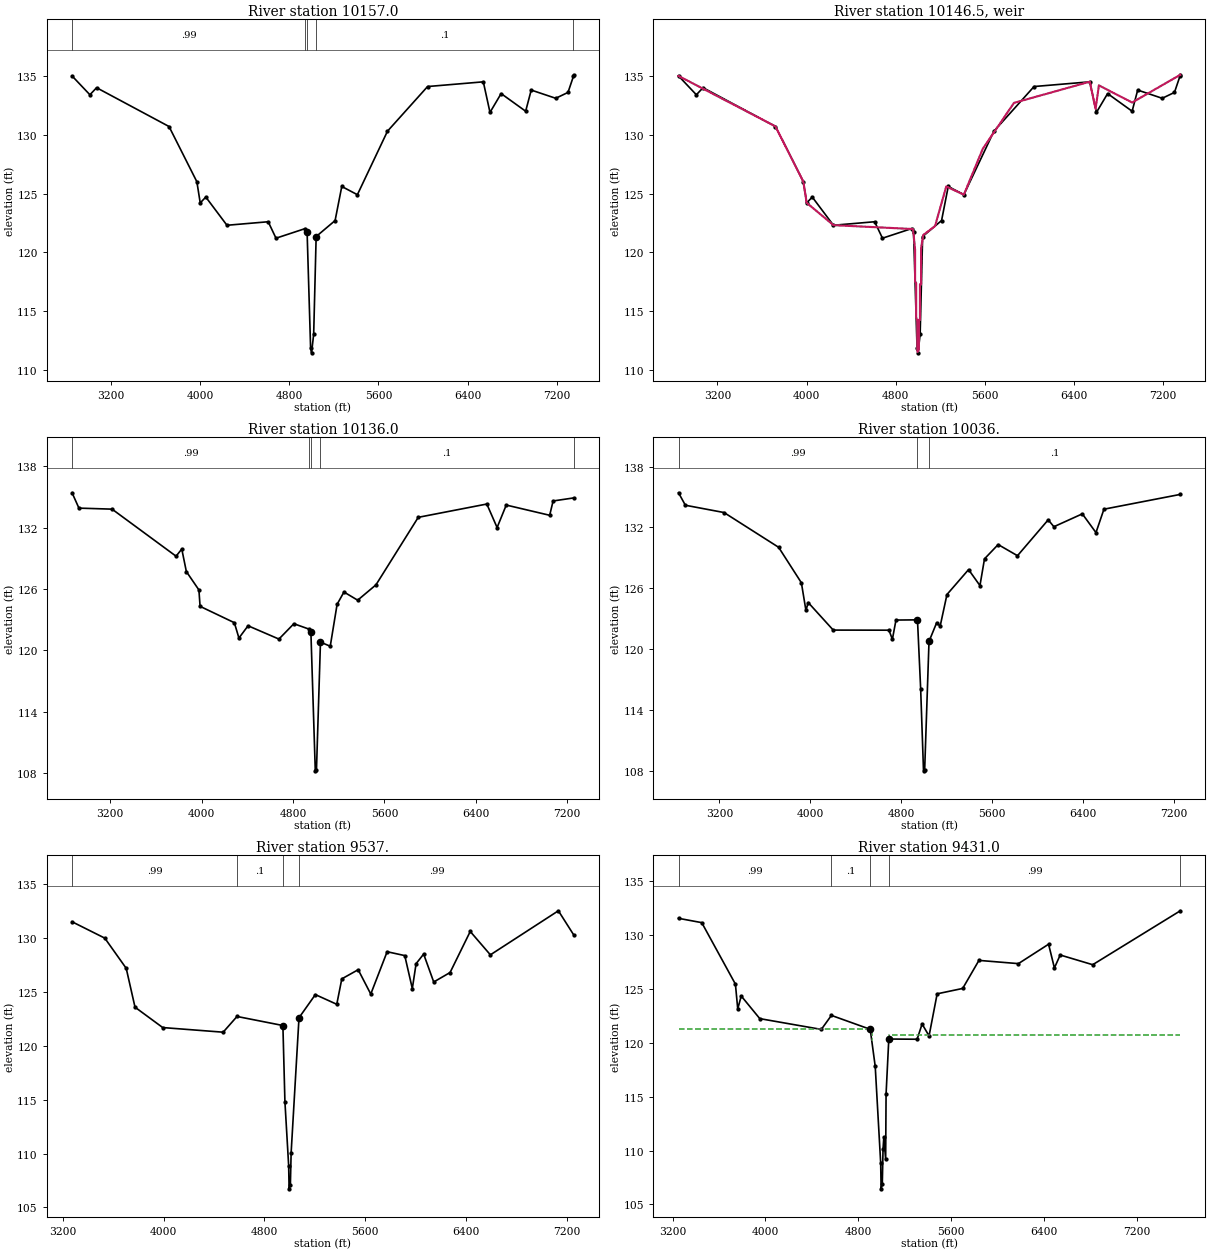
Type RM Length L Ch R = 1 ,10157.0 ,22,21,17.4
BEGIN DESCRIPTION:
Upstream Section of Bridge/Culvert/Weir
END DESCRIPTION:
XS GIS Cut Line= 5
      3066945.73     13939617.51      3065655.31     13938260.41
      3065507.59     13938184.26      3065317.61     13938091.44
      3063776.61     13936448.39
#Sta/Elev= 30
  2850.7     135  3010.7   133.4  3070.7     134  3720.7   130.7  3970.7     126
  4000.7   124.2  4050.7   124.7  4240.7   122.3  4610.7   122.6  4680.7   121.2
  4943.2  122.02  4959.9   121.7  4991.1  111.89  4999.8  111.45  5018.8  113.03
    5041  121.34    5211   122.7    5271   125.6    5411   124.9    5681   130.3
    6041   134.1    6541   134.5    6601   131.9    6701   133.5    6921     132
    6971   133.8    7191   133.1    7301   133.6  7349.8  134.97  7353.6   135.1
#Mann= 5 ,-1 , 0
  2850.7     .99       0  4943.2     .06       0  4959.9     .03       0
    5041      .1       0  7349.8      .2       0
#XS Ineff= 2 , 0
       0  4959.9   121.7    5041       0  121.34
Permanent Ineff=
       F       F
Bank Sta=4959.9,5041
XS Rating Curve= 0
Exp/Cntr=.7,.5

Type RM Length L Ch R = 5 ,10146.5 ,,,
BEGIN DESCRIPTION:
DAM 90' DS THEISWOOD DRIVE
Structure ID: K131-02-00-S6
END DESCRIPTION:
IW Pilot Flow=0
#Inline Weir SE= 30
  2850.7     135  3720.7  130.71  3970.7  126.01  4000.7  124.21  4240.7  122.31
  4955.3  121.98  4973.2  120.25  4973.6  117.54  4983.3  117.38  4983.6  114.47
  4993.5  114.17  4993.9  111.71  4996.5  111.52  5006.8  111.71  5007.8  114.26
  5017.3  114.24  5017.4  117.28  5027.1  117.25  5027.4  120.31  5045.3  121.46
  5152.9  122.24  5252.9   125.6    5411   124.9    5581  128.81    5861  132.71
    6541  134.51  6592.9   132.2  6622.9   134.2    6921  132.74  7353.6   135.1
IW Dist,WD,Coef,Skew,MaxSub,Min_El,Is_Ogee,SpillHt,DesHd
10,1,3,0,.95,, 0 ,,,0,0,

Type RM Length L Ch R = 1 ,10136.0 ,105.2,100,99
BEGIN DESCRIPTION:
Cross Section FIELD_DS
Located At: DAM 90' DS THEISWOOD DRIVE
END DESCRIPTION:
XS GIS Cut Line= 5
      3066986.62     13939542.54      3065687.03     13938252.94
      3065509.33     13938163.44      3065347.11      13938087.1
      3063899.29      13936455.2
#Sta/Elev= 30
  2866.6   135.4  2926.6   133.9  3216.6   133.8  3776.6   129.2  3826.6   129.9
  3866.6   127.7  3976.6   125.9  3986.6   124.3  4286.6   122.7  4326.6   121.2
  4406.6   122.4  4676.6   121.1  4807.4   122.6  4938.2  122.08  4956.3   121.8
  4994.8  108.22    5005  108.26  5040.1   120.8  5125.7   120.4  5185.7   124.5
  5245.7   125.7  5365.7   124.9  5525.7   126.4  5895.7     133  6495.7   134.3
  6585.7     132  6665.7   134.2  7045.7   133.2  7075.7   134.6  7257.3   134.9
#Mann= 5 ,-1 , 0
  2866.6     .99       0  4938.2     .06       0  4956.3     .03       0
  5040.1      .1       0  7257.3     .99       0
#XS Ineff= 2 , 0
       0  4956.3   121.8  5040.1       0   120.8
Permanent Ineff=
       F       F
Bank Sta=4956.3,5040.1
XS Rating Curve= 0
Exp/Cntr=.7,.5

Type RM Length L Ch R = 1 ,10036.  ,365.2,499,558.6
BEGIN DESCRIPTION:
DAM-S6_DS FIELD - XS 1
END DESCRIPTION:
XS GIS Cut Line= 5
       3067001.7       13939522.      3065674.32     13938174.18
      3065554.02     13938070.33       3065391.8     13937993.99
      3063943.98     13936362.09
#Sta/Elev= 30
  2841.4  135.41  2901.4  134.18  3241.4  133.46  3721.4  130.03  3921.4  126.53
  3961.4   123.8  3981.4  124.58  4201.4  121.86  4691.4  121.85  4721.4  120.95
  4753.1  122.85  4942.1  122.87 4970.02  116.07  4995.1  107.97 5005.26  108.06
 5043.44  120.74  5111.3   122.6  5141.3  122.24  5201.3  125.37  5391.3  127.83
  5491.3  126.25  5531.3  128.89  5651.3   130.3  5821.3   129.2  6091.3  132.74
  6141.3  132.06  6391.3  133.33  6511.3  131.48  6581.3  133.79  7252.9  135.25
#Mann= 3 ,-1 , 0
  2841.4     .99       0  4942.1     .03       0 5043.44      .1       0
Bank Sta=4942.1,5043.44
XS Rating Curve= 0
Exp/Cntr=.3,.1

Type RM Length L Ch R = 1 ,9537.   ,60.3,106,162.1
BEGIN DESCRIPTION:
VETERANS MEMORIAL_US - XS 4
END DESCRIPTION:
XS GIS Cut Line= 5
      3066568.37      13939074.5      3065666.39     13938077.65
      3065839.62     13937792.02      3065814.49     13937680.95
      3064445.63     13935967.67
#Sta/Elev= 30
  3272.8  131.51  3532.8  129.99  3702.8  127.19  3772.8  123.58  3992.8  121.69
  4472.8  121.26  4582.8  122.72  4947.2  121.88 4963.32  114.81 4993.02  108.86
 4996.58  106.72 5006.62  107.08 5012.66  110.07  5075.1   122.6  5205.1  124.75
  5375.1  123.85  5415.1  126.21  5545.1  127.06  5645.1   124.8  5775.1  128.73
  5915.1  128.37  5975.1  125.31  6005.1  127.62  6065.1  128.51  6145.1  125.92
  6275.1   126.8  6435.1  130.61  6595.1  128.44  7135.1  132.53  7258.1  130.27
#Mann= 4 ,-1 , 0
  3272.8     .99       0  4582.8      .1       0  4947.2     .04       0
  5075.1     .99       0
Bank Sta=4947.2,5075.1
XS Rating Curve= 0
Exp/Cntr=.5,.3

Type RM Length L Ch R = 1 ,9431.0  ,141.6,120,117
BEGIN DESCRIPTION:
Upstream Section of Bridge/Culvert/Weir
END DESCRIPTION:
XS GIS Cut Line= 6
      3066573.43     13939072.28      3065709.59     13938078.25
      3065877.21     13937793.02      3065974.37     13937617.79
      3066154.56     13937329.86      3064542.47     13935930.42
#Sta/Elev= 30
  3251.7  131.533451.699  131.133741.699  125.433761.701  123.13  3791.7  124.33
  3951.7  122.234481.701  121.23  4568.6  122.53    4903  121.24  4946.1   117.8
    4993  108.86  4996.9  106.45  5006.9  106.875013.299  110.125020.102  111.24
  5035.9  109.19  5039.5  115.24    5063  120.34  5306.9  120.32  5349.8  121.73
5409.798  120.63  5479.5  124.53  5699.5  125.03  5839.5  127.63  6179.5  127.33
  6439.5  129.13  6489.5  126.93  6539.5  128.13  6819.5  127.23  7574.3  132.23
#Mann= 5 ,-1 , 0
  3251.7     .99       0  4568.6      .1       0    4903     .04       0
    5063     .99       0  7574.3     .99       0
#XS Ineff= 2 , 0
       0 4916.12  121.24 5062.62       0  120.75
Permanent Ineff=
       F       F
Bank Sta=4903,5063
XS Rating Curve= 0
Exp/Cntr=.5,.3

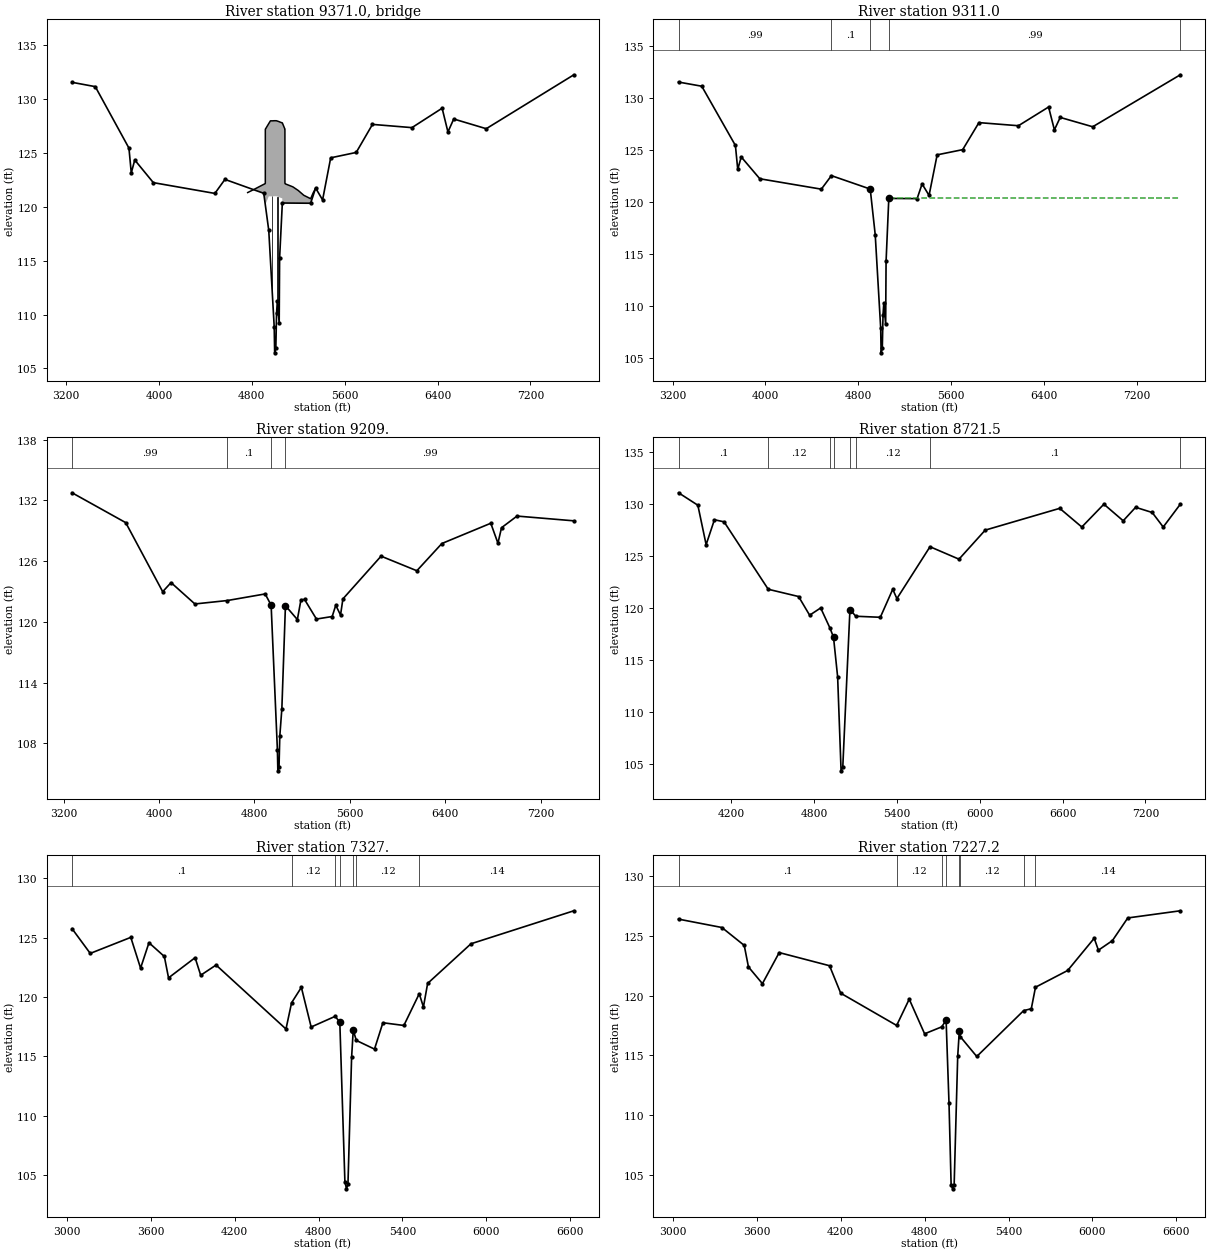
Type RM Length L Ch R = 3 ,9371.0  ,,,
BEGIN DESCRIPTION:
Stuebner-Airline Road
Structure ID: K131-02-00-S5
END DESCRIPTION:
Bridge Culvert--1,0,-1,-1, 0
Deck Dist Width WeirC Skew NumUp NumDn MinLoCord MaxHiCord MaxSubmerge Is_Ogee
10,100,2.6,0, 40, 40, , , .95, 0, ,,,
  4764.54816.601 4902.51 4902.634902.6994903.0094914.0994916.3914916.499 4916.61
  4946.14960.399  4982.1  4990.9 4992.99  4996.9 4998.71    5005  5006.9  5011.7
5013.2995020.101  5035.95039.509 5062.47 5062.595062.701    5063  5063.15085.189
  5085.3 5085.41    50885153.609  5200.5  5212.1  5247.5 5306.91  5329.8  5349.8
  121.31  121.59  122.07  122.07  122.07  122.07  122.13  122.18  127.18  127.18
  127.71  127.96  127.96  127.97  127.97  127.97  127.97  127.97  127.97  127.97
  127.96  127.94  127.88  127.86  127.77  127.77  127.77  127.77  127.77  127.19
  127.19  122.19  122.12  121.84   121.5  121.39  121.06  120.74  121.31  121.71
   121.3  121.26  121.21  121.21  121.21     120  120.12  120.18  120.18  120.18
  120.96  120.96  120.96  120.97  120.97  120.97  120.97  120.97  120.97  120.97
  120.96  120.94  120.88  120.86  120.77  120.77  120.24  120.31  120.33  120.33
  120.33  120.33  120.33  120.32  120.31  120.31   120.3  120.29   121.3   121.7
  4764.54816.601 4902.51 4902.634902.6994903.0094914.0994916.3914916.499 4916.61
  4946.14960.399  4982.1  4990.9 4992.99  4996.9 4998.71    5005  5006.9  5011.7
5013.2995020.101  5035.95039.509 5062.47 5062.595062.701    5063  5063.15085.189
  5085.3 5085.41    50885153.609  5200.5  5212.1  5247.5 5306.91  5329.8  5349.8
  121.31  121.59  122.07  122.07  122.07  122.07  122.13  122.18  127.18  127.18
  127.71  127.96  127.96  127.97  127.97  127.97  127.97  127.97  127.97  127.97
  127.96  127.94  127.88  127.86  127.77  127.77  127.77  127.77  127.77  127.19
  127.19  122.19  122.12  121.84   121.5  121.39  121.06  120.74  121.31  121.71
   121.3  121.26  121.21  121.21  121.21     120  120.12  120.18  120.18  120.18
  120.71  120.96  120.96  120.97  120.97  120.97  120.97  120.97  120.97  120.97
  120.96  120.94  120.88  120.86  120.77  120.77  120.24  120.31  120.33  120.33
  120.33  120.33  120.33  120.32  120.31  120.31   120.3  120.29   121.3   121.7
Pier Skew, UpSta & Num, DnSta & Num=  ,4975.899, 2 ,4975.899, 2 , 0 , 0 , 0 ,,
     1.3     1.3
  110.83  121.96
     1.3     1.3
  110.83  121.96
Pier Skew, UpSta & Num, DnSta & Num=  ,5020.899, 2 ,5020.899, 2 , 0 , 0 , 0 ,,
     1.3     1.3
  110.02  121.94
     1.3     1.3
  110.02  121.94
BR Coef= 1 , 1 , 1 ,1.25, 0 ,,,.8,0,2,0,
WSPro=,,,, 1 ,,,, 0 ,,,, 0 ,,,,-1 ,-1 ,-1 , 0 , 0 , 0 , 0 , 0
BC Design=,, 0 ,, 0 ,,,,,,

Type RM Length L Ch R = 1 ,9311.0  ,103.9,102,101
BEGIN DESCRIPTION:
Downstream Section of Bridge/Culvert/Weir
END DESCRIPTION:
XS GIS Cut Line= 6
       3066676.3     13939097.12      3065821.89     13938113.94
      3065982.35     13937840.89      3066079.38      13937665.9
      3066268.36     13937363.93      3064643.35     13935953.28
#Sta/Elev= 30
  3251.7  131.533451.699  131.133741.699  125.433761.701  123.13  3791.7  124.33
  3951.7  122.234481.701  121.23  4568.6  122.53    4903  121.24  4946.1  116.84
    4993   107.9  4996.9  105.49  5006.9  105.91  5013.3  109.16  5020.1  110.28
  5035.9  108.23  5039.5  114.28    5063  120.34  5306.9  120.32  5349.8  121.73
5409.798  120.63  5479.5  124.53  5699.5  125.03  5839.5  127.63  6179.5  127.33
  6439.5  129.13  6489.5  126.93  6539.5  128.13  6819.5  127.23  7574.3  132.23
#Mann= 5 ,-1 , 0
  3251.7     .99       0  4568.6      .1       0    4903     .04       0
    5063     .99       0  7574.3     .99       0
#XS Ineff= 2 , 0
       04909.556  120.03 5063.33       0  120.36
Permanent Ineff=
       F       F
Bank Sta=4903,5063
XS Rating Curve= 0
Exp/Cntr=.5,.3

Type RM Length L Ch R = 1 ,9209.   ,587.5,487.5,396.5
BEGIN DESCRIPTION:
VETERANS MEMORIAL_DS - XS 1
END DESCRIPTION:
XS GIS Cut Line= 6
       3066769.4      13939141.8      3065915.01     13938158.63
      3066075.47     13937885.59      3066172.49      13937710.6
      3066282.35     13937365.68      3064812.82     13935970.07
#Sta/Elev= 30
    3271  132.74    3721  129.79    4031  122.97    4101  123.87    4301  121.76
  4573.6   122.1  4890.3  122.75  4940.3  121.64 4993.02  107.32 4996.64  105.28
 5006.59  105.68 5012.96   108.7  5030.3  111.42  5060.3  121.59  5160.3  120.22
  5190.3  122.16  5220.3  122.21  5320.3  120.27  5452.3  120.52  5482.3  121.63
  5522.3  120.67  5542.3  122.26  5862.3  126.48  6162.3  125.04  6372.3  127.73
  6782.3  129.73  6842.3  127.76  6872.3  129.29  7002.3  130.44    7479  129.97
#Mann= 4 ,-1 , 0
    3271     .99       0  4573.6      .1       0  4940.3     .04       0
  5060.3     .99       0
Bank Sta=4940.3,5060.3
XS Rating Curve= 0
Exp/Cntr=.3,.1

Type RM Length L Ch R = 1 ,8721.5  ,1388.5,1394.5,1394.7
BEGIN DESCRIPTION:
Cross Section K131-02-00-X5
END DESCRIPTION:
XS GIS Cut Line= 4
      3067388.72     13938397.57      3066586.75     13937646.41
      3066391.57     13937469.45      3064846.61     13935800.93
#Sta/Elev= 30
  3817.5   131.1  3957.5   129.9  4017.5   126.1  4077.5   128.5  4147.5   128.3
  4467.5   121.8  4687.5   121.1  4767.5   119.3  4847.5     120  4915.2  118.05
  4940.5  117.18  4970.4  113.36  4995.4   104.3  5007.8  104.69  5059.7  119.85
  5101.9   119.2  5279.8   119.1  5369.8   121.8  5399.8   120.9  5639.8   125.9
  5849.8   124.7  6039.8   127.5  6579.8   129.6  6739.8   127.8  6899.8     130
  7039.8   128.4  7129.8   129.7  7249.8   129.2  7329.8   127.8  7453.7     130
#Mann= 8 ,-1 , 0
  3817.5      .1       0  4467.5     .12       0  4915.2     .06       0
  4940.5     .04       0  5059.7     .06       0  5101.9     .12       0
  5639.8      .1       0  7453.7      .2       0
Bank Sta=4940.5,5059.7
XS Rating Curve= 0
Exp/Cntr=.3,.1

Type RM Length L Ch R = 1 ,7327.   ,98,99.8,104
BEGIN DESCRIPTION:
DAM-S6B_US FIELD - XS 4
END DESCRIPTION:
XS GIS Cut Line= 6
      3068760.24       13938173.        3067585.     13936702.94
      3067549.33      13936666.1      3067507.69     13936619.26
      3067487.74     13936601.04      3066333.99     13935542.29
#Sta/Elev= 30
  3037.4  125.76  3167.4  123.68  3457.4  125.03  3527.4  122.44  3587.4  124.58
  3697.4  123.42  3727.4  121.62  3917.4  123.32  3957.4  121.84  4067.4   122.7
  4567.4  117.31  4607.4  119.52  4677.4  120.82  4747.4  117.48  4919.5  118.38
 4952.44  117.88 4988.74  104.46 5000.16  103.85 5010.71  104.26 5036.73  114.92
 5048.41  117.21  5070.5  116.35  5200.5  115.62  5260.5  117.84  5410.5  117.61
  5520.5  120.28  5550.5  119.17  5580.5  121.15  5890.5  124.49  6626.4  127.27
#Mann= 7 ,-1 , 0
  3037.4      .1       0  4607.4     .12       0  4919.5     .06       0
 4952.44     .04       0 5048.41     .06       0  5070.5     .12       0
  5520.5     .14       0
Bank Sta=4952.44,5048.41
XS Rating Curve= 0
Exp/Cntr=.7,.5

Type RM Length L Ch R = 1 ,7227.2  ,19,20.5,22.5
BEGIN DESCRIPTION:
Upstream Section of Bridge/Culvert/Weir
END DESCRIPTION:
XS GIS Cut Line= 6
      3068838.45     13938105.95      3067663.21      13936635.9
      3067627.55     13936599.06      3067585.91     13936552.22
      3067565.96       13936534.       3066412.2     13935475.25
#Sta/Elev= 30
  3039.5   126.4  3349.5   125.7  3509.5   124.2  3539.5   122.4  3639.5     121
  3759.5   123.6  4119.5   122.5  4199.5   120.2  4599.5   117.5  4689.5   119.7
  4799.5   116.8  4921.5  117.38  4953.3  117.93    4974  110.99  4989.2  104.14
  5000.5  103.82  5010.8  104.16  5036.2   114.9  5047.6  117.02  5054.1  116.57
  5172.6   114.9  5507.8  118.74  5562.6   118.9  5592.6   120.7  5822.6   122.1
  6012.6   124.8  6042.6   123.8  6142.6   124.6  6252.6   126.5  6628.5   127.1
#Mann= 8 ,-1 , 0
  3039.5      .1       0  4599.5     .12       0  4921.5     .06       0
  4953.3     .04       0  5047.6     .06       0  5054.1     .12       0
  5507.8    .045       0  5592.6     .14       0
#XS Ineff= 2 , 0
       0  4953.3   116.9  5047.6       0  114.91
Permanent Ineff=
       F       F
Bank Sta=4953.3,5047.6
XS Rating Curve= 0
Exp/Cntr=.7,.5