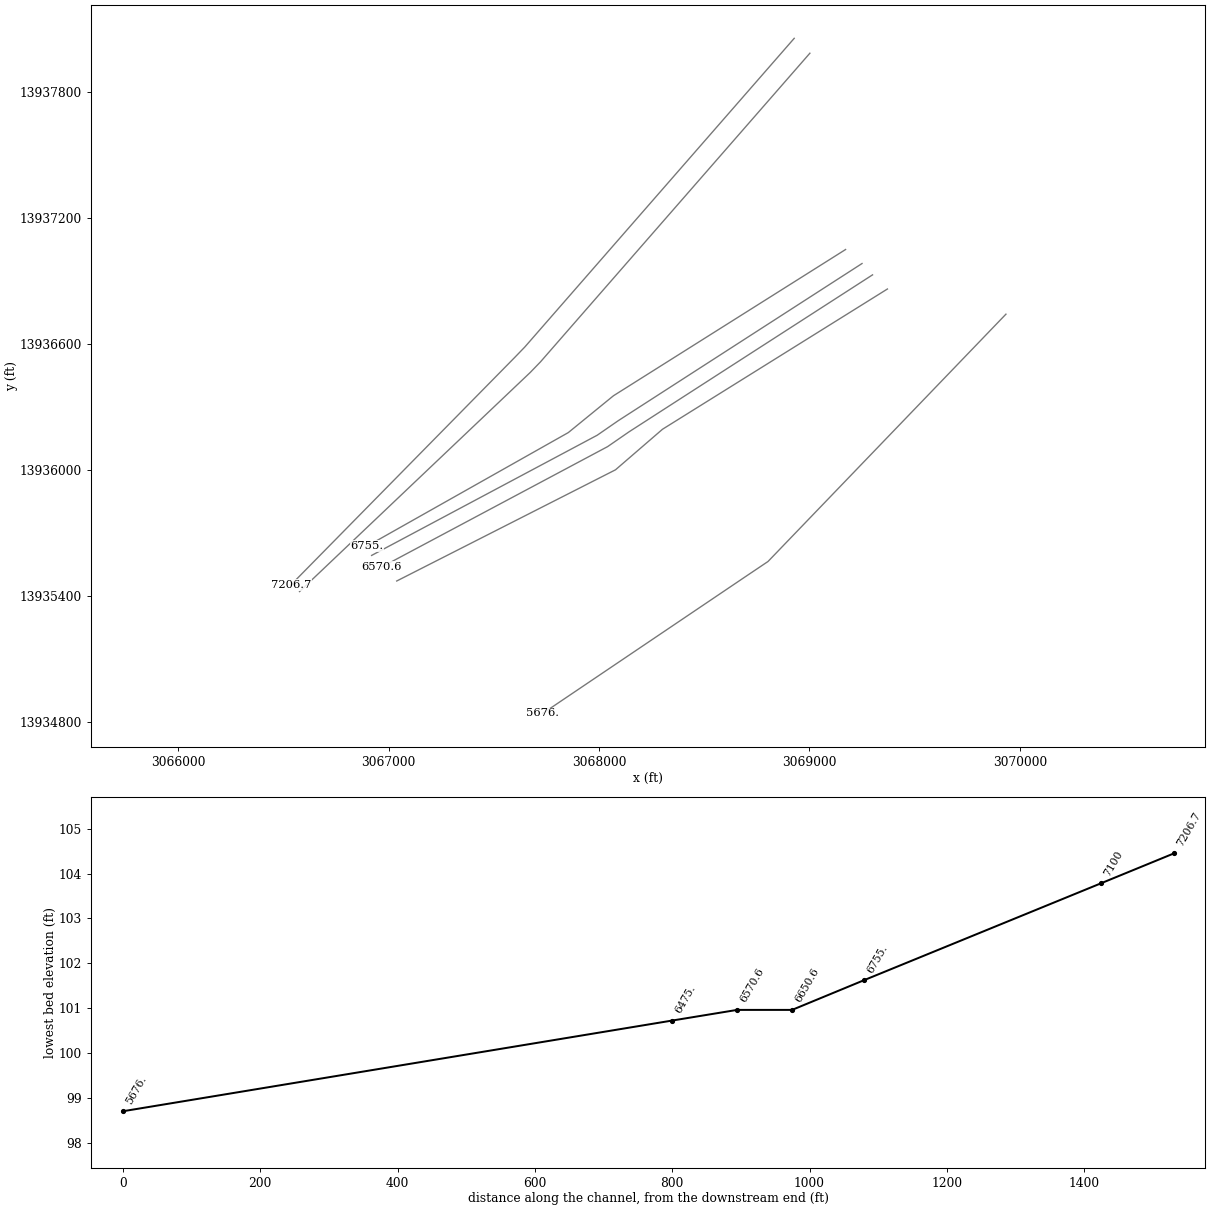
HEC-RAS study K131-02-00.prj: K131-02-00

--- K131-02-00.g01 (geometry) --- (continued)

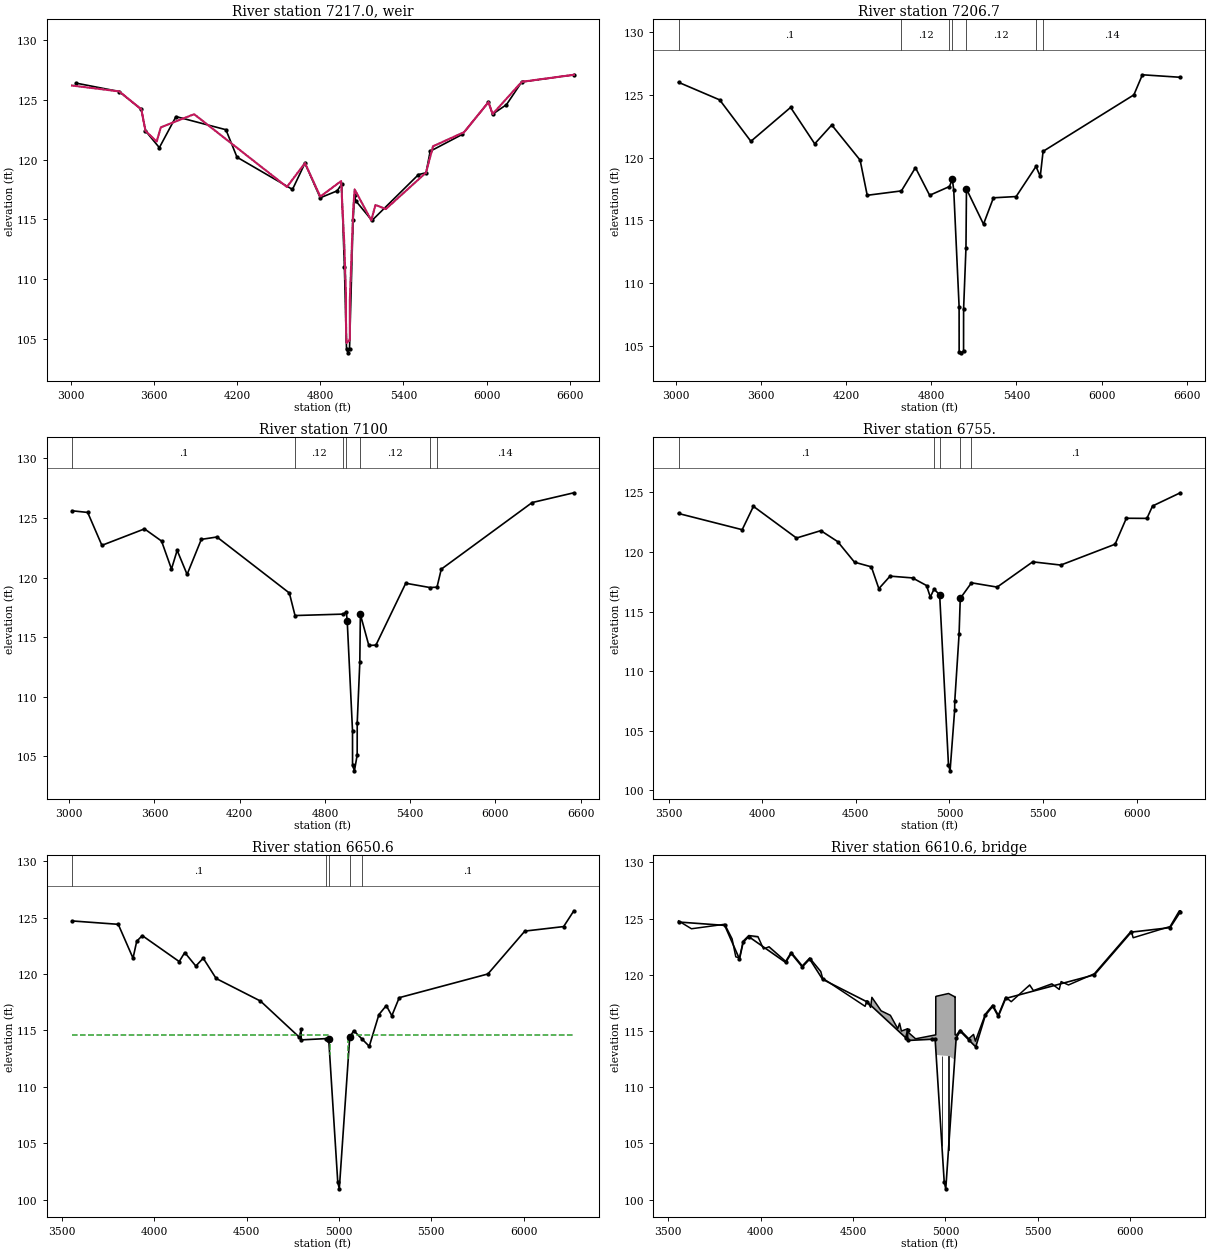
Type RM Length L Ch R = 5 ,7217.0  ,,,
BEGIN DESCRIPTION:
DROP STRUCTURE 600' US OAKWOOD GLEN
Structure ID: K131-02-00-S6B
END DESCRIPTION:
IW Pilot Flow=0
#Inline Weir SE= 30
  3010.1   126.2  3349.5  125.71  3509.5  124.21  3539.5  122.41  3620.1   121.5
  3650.1   122.7  3890.1   123.8  4559.5  117.71  4689.5  119.71  4800.1   116.9
  4950.1   118.2  4972.8     113    4985  108.74  4985.1  106.46  4989.2  104.64
  5012.2   104.9  5013.1  105.25  5013.4  108.28  5037.8   115.9  5047.8   117.5
  5167.8  114.91  5197.8   116.2  5272.6  115.86  5562.6  118.91  5612.6  121.11
  5837.8   122.3  6012.6  124.81  6042.6  123.81  6252.6  126.51  6628.5   127.1
IW Dist,WD,Coef,Skew,MaxSub,Min_El,Is_Ogee,SpillHt,DesHd
10,1,3,0,.95,, 0 ,,,0,0,

Type RM Length L Ch R = 1 ,7206.7  ,110,106.7,102.7
BEGIN DESCRIPTION:
Cross Section FIELD_DS
Located At: DROP STRUCTURE 600' US OAKWOOD GLEN
END DESCRIPTION:
XS GIS Cut Line= 4
      3068927.96     13938057.83      3067647.41     13936587.49
      3067598.83     13936537.17      3066535.78     13935454.38
#Sta/Elev= 30
  3018.1     126  3308.1   124.6  3528.1   121.3  3808.1     124  3978.1   121.1
  4098.1   122.6  4298.1   119.8  4348.1     117  4589.2  117.35  4688.1   119.2
  4788.1     117  4928.1   117.7    4948   118.3  4958.1   117.4  4995.8  108.14
  4996.1  104.54  5009.5  104.45  5027.2  104.61  5027.5  107.94  5044.2  112.81
  5047.7   117.5  5167.8   114.7  5237.8   116.8  5397.8   116.9  5537.8   119.3
  5567.8   118.5  5587.8   120.5  6227.8     125  6287.8   126.6  6555.2   126.4
#Mann= 7 ,-1 , 0
  3018.1      .1       0  4589.2     .12       0  4928.1     .06       0
    4948     .03       0  5047.7     .12       0  5537.8    .045       0
  5587.8     .14       0
#XS Ineff= 2 , 0
       0                  5047.6       0   114.9
Permanent Ineff=
       F       F
Bank Sta=4948,5047.7
XS Rating Curve= 0
Exp/Cntr=.7,.5

Type RM Length L Ch R = 1 ,7100    ,360.3,345,336.4
BEGIN DESCRIPTION:
DAM-S6B_DS FIELD - XS 1
END DESCRIPTION:
XS GIS Cut Line= 4
      3069002.45       13937987.       3067721.9     13936516.72
      3067673.32     13936466.41      3066576.84     13935422.84
#Sta/Elev= 30
  3019.8   125.6  3129.8  125.46  3229.8   122.7  3529.8  124.08  3649.8  123.06
  3719.8  120.71  3759.8  122.28  3829.8  120.26  3929.8   123.2  4039.8   123.4
  4549.8   118.7  4589.8  116.81  4929.8  116.93 4950.82  117.12 4957.32  116.34
 4994.55  107.16 4994.85  104.24 5008.08  103.78  5027.4  105.11 5027.73  107.82
 5045.95  112.88 5049.87   116.9  5109.5   114.3  5159.5  114.33  5369.5  119.52
  5539.5  119.16  5589.5  119.19  5619.5   120.7  6259.5  126.29  6553.2  127.11
#Mann= 7 ,-1 , 0
  3019.8      .1       0  4589.8     .12       0  4929.8     .06       0
 4950.82     .03       0 5049.87     .12       0  5539.5    .045       0
  5589.5     .14       0
Bank Sta=4957.32,5049.87
XS Rating Curve= 0
Exp/Cntr=.3,.1

Type RM Length L Ch R = 1 ,6755.   ,110.2,104.4,90.2
BEGIN DESCRIPTION:
OAKWOOD GLEN_US - XS 4
END DESCRIPTION:
XS GIS Cut Line= 4
       3069172.1       13937052.      3068068.93     13936355.49
       3067854.4     13936180.15      3066898.22     13935639.54
#Sta/Elev= 30
  3553.1  123.23  3893.1  121.87  3953.1  123.83  4183.1  121.17  4313.1  121.79
  4403.1  120.87  4493.1  119.14  4583.1  118.75  4623.1  116.92  4683.1  117.97
  4803.1  117.82  4877.9  117.18  4897.9  116.21  4917.9  116.88  4947.9   116.4
 4994.98  102.12 5003.49  101.62 5028.04  106.74 5028.46  107.45 5051.62  113.09
  5057.9   116.1  5117.9  117.41    5255  117.05    5445  119.17    5595   118.9
    5885  120.65    5945  122.83    6055  122.82    6085  123.86  6233.4  124.97
#Mann= 5 ,-1 , 0
  3553.1      .1       0  4917.9     .06       0  4947.9     .04       0
  5057.9     .06       0  5117.9      .1       0
Bank Sta=4947.9,5057.9
XS Rating Curve= 0
Exp/Cntr=.5,.3

Type RM Length L Ch R = 1 ,6650.6  ,74.5,80,81
BEGIN DESCRIPTION:
Upstream Section of Bridge/Culvert/Weir
END DESCRIPTION:
XS GIS Cut Line= 4
      3069250.33     13936985.29      3068091.99     13936236.95
       3067991.6     13936167.45      3066919.49     13935594.97
#Sta/Elev= 30
  3555.4   124.7  3805.4   124.4  3885.4   121.4  3905.4   122.9  3935.4   123.4
  4135.4   121.1  4165.4   121.9  4225.4   120.7  4265.4   121.4  4335.4   119.6
  4575.4   117.6  4785.4   114.4  4795.4   115.1  4795.8  114.16  4928.2  114.27
  4944.6  114.26  4993.7  101.57  5002.1  100.96  5058.5  114.38  5080.2  114.98
  5126.6  114.21  5164.3  113.59  5216.5   116.4  5256.5   117.2  5286.5   116.3
  5326.5   117.9  5806.5     120  6006.5   123.8  6216.5   124.2  6271.9   125.6
#Mann= 5 ,-1 , 0
  3555.4      .1       0  4928.2     .06       0  4944.6     .04       0
  5058.5     .06       0  5126.6      .1       0
#XS Ineff= 2 , 0
       0  4950.2  114.57 5050.34       0  114.62
Permanent Ineff=
       F       F
Bank Sta=4944.6,5058.5
XS Rating Curve= 0
Exp/Cntr=.5,.3

Type RM Length L Ch R = 3 ,6610.6  ,,,
BEGIN DESCRIPTION:
OAKWOOD GLEN- deck width was 105, reduced to 60 based on aerial VRR
Structure ID: K131-02-00-S4
END DESCRIPTION:
Bridge Culvert--1,0,-1,-1, 0
Deck Dist Width WeirC Skew NumUp NumDn MinLoCord MaxHiCord MaxSubmerge Is_Ogee
10,60,2.6,0, 60, 60, , , .95, 0, ,,,
  3555.4  3625.4  3805.4  3845.4  3865.4  3885.4  3905.4  3935.4  3985.4  4015.4
  4045.4  4135.4  4165.4  4225.4  4265.4  4325.4  4335.4  4565.4  4575.4  4595.4
  4602.1  4652.1  4702.1  4742.1  4752.1  4762.1  4785.4  4795.4  4795.8  4838.8
  4944.6 4947.89    4948 4949.95  5017.1  5050.4  5052.6 5052.71  5058.5  5080.2
  5126.6  5152.4  5162.4  5216.5  5256.5  5286.5  5326.5  5356.5  5456.5  5476.5
  5576.5  5616.5  5626.5  5666.5  5806.5  6006.5  6016.5  6216.5  6266.5  6271.9
   124.8   124.1   124.5   123.2   121.6   121.5     123   123.5   123.4   122.3
   122.5   121.2     122   120.8   121.5   120.3   119.7   117.2   117.7   117.1
     118   116.8   116.4  115.21   115.7     115  115.14  115.21  114.93  114.31
  114.65  114.66  118.06  118.09  118.34  118.05  118.07  114.67  114.62  115.09
  114.32   114.7   114.1  116.51  117.31  116.41  118.01  117.61   119.1   118.6
   119.2   118.7   119.4   119.1   120.1   123.9   123.3   124.3   125.7   125.7
  124.64  123.94  124.34  123.04  121.44  121.34  122.84  123.34  123.24  122.14
  122.34  121.04  121.84  120.64  121.34  120.14  119.54  117.04  117.54  116.94
  116.88  116.47  115.69  115.04  114.88  114.72  114.34  115.04   114.1  114.14
   114.2  113.37  113.34  112.85  112.78  112.41  112.93  112.95  114.32  114.92
  114.15  113.73  113.56  116.34  117.14  116.24  117.84  117.44  118.94  118.44
  119.04  118.54  119.24  118.94  119.94  123.74  123.14  124.14  125.54  125.54
  3555.4  3625.4  3805.4  3845.4  3865.4  3885.4  3905.4  3935.4  3985.4  4015.4
  4045.4  4135.4  4165.4  4225.4  4265.4  4325.4  4335.4  4565.4  4575.4  4595.4
  4602.1  4652.1  4702.1  4742.1  4752.1  4762.1  4785.4  4795.4  4795.8  4838.8
  4944.6 4947.89    4948 4949.95  5017.1  5050.4  5052.6 5052.71  5058.5  5080.2
  5126.6  5152.4  5162.4  5216.5  5256.5  5286.5  5326.5  5356.5  5456.5  5476.5
  5576.5  5616.5  5626.5  5666.5  5806.5  6006.5  6016.5  6216.5  6266.5  6271.9
   124.8   124.1   124.5   123.2   121.6   121.5     123   123.5   123.4   122.3
   122.5   121.2     122   120.8   121.5   120.3   119.7   117.2   117.7   117.1
     118   116.8   116.4  115.21   115.7     115  115.14  115.21  114.93  114.31
  114.65  114.66  118.06  118.09  118.34  118.05  118.07  114.67  114.62  115.09
  114.32   114.7   114.1  116.51  117.31  116.41  118.01  117.61   119.1   118.6
   119.2   118.7   119.4   119.1   120.1   123.9   123.3   124.3   125.7   125.7
  124.64  123.94  124.34  123.04  121.44  121.34  122.84  123.34  123.24  122.14
  122.34  121.04  121.84  120.64  121.34  120.14  119.54  117.04  117.54  116.94
  116.88  116.47  115.69  115.04  114.88  114.72  114.34  115.04   114.1  114.14
   114.2  113.37  113.34  112.85  112.78  112.41  112.93  112.95  114.32  114.92
  114.15  113.73  113.56  116.34  117.14  116.24  117.84  117.44  118.94  118.44
  119.04  118.54  119.24  118.94  119.94  123.74  123.14  124.14  125.54  125.54
Pier Skew, UpSta & Num, DnSta & Num=  ,4981.4, 2 ,4981.4, 2 , 0 , 0 , 0 ,,
     1.1     1.1
  103.75  113.84
     1.1     1.1
  104.07  114.16
Pier Skew, UpSta & Num, DnSta & Num=  ,5016.6, 2 ,5016.6, 2 , 0 , 0 , 0 ,,
     1.1     1.1
  103.29  113.78
     1.1     1.1
  103.61   114.1
BR Coef= 1 , 1 , 1 ,1.25, 0 ,,,.8,0,2,0,
WSPro=,,,, 1 ,,,, 0 ,,,, 0 ,,,,-1 ,-1 ,-1 , 0 , 0 , 0 , 0 , 0
BC Design=,, 0 ,, 0 ,,,,,,

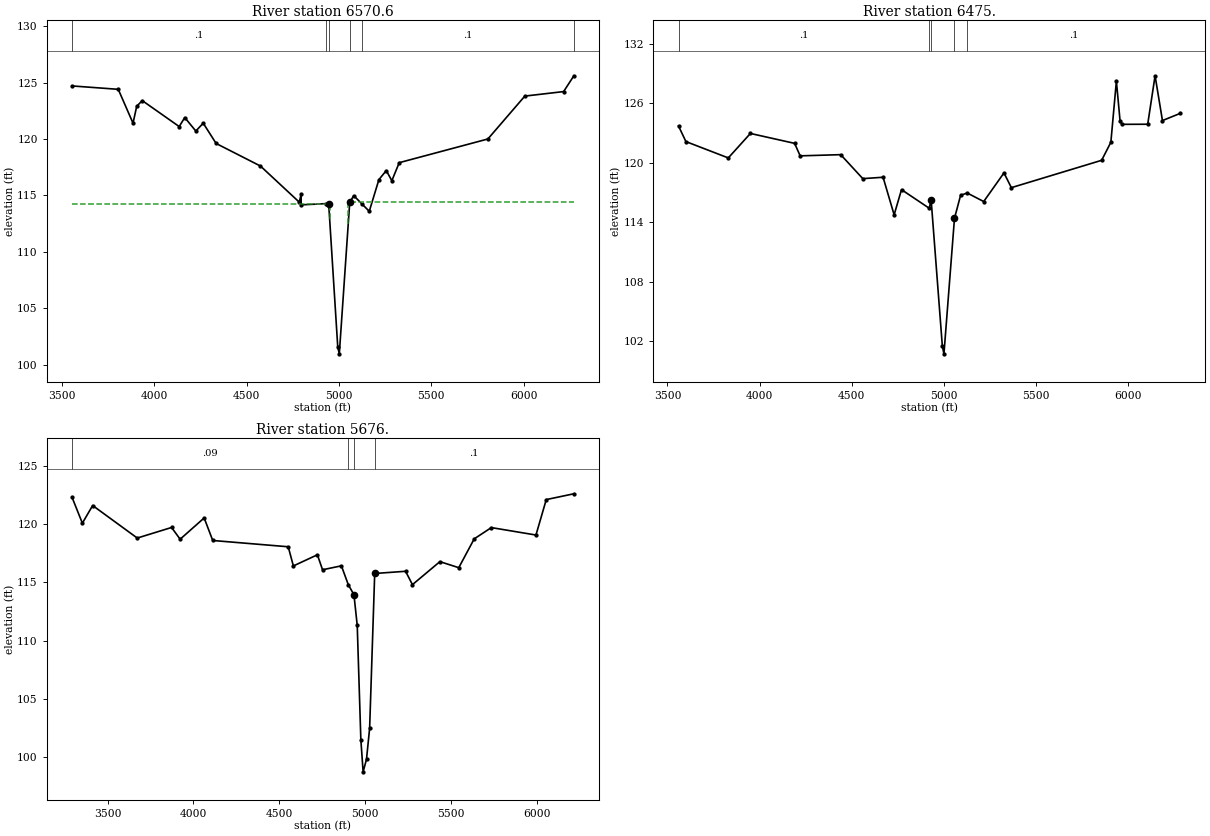
Type RM Length L Ch R = 1 ,6570.6  ,91,95.6,115.5
BEGIN DESCRIPTION:
Downstream Section of Bridge/Culvert/Weir
END DESCRIPTION:
XS GIS Cut Line= 4
      3069300.26     13936931.34      3068142.19     13936183.18
      3068041.11      13936113.2      3066967.99     13935540.18
#Sta/Elev= 30
  3555.4   124.7  3805.4   124.4  3885.4   121.4  3905.4   122.9  3935.4   123.4
  4135.4   121.1  4165.4   121.9  4225.4   120.7  4265.4   121.4  4335.4   119.6
  4575.4   117.6  4785.4   114.4  4795.4   115.1  4795.8  114.16  4928.2  114.27
  4944.6  114.26  4993.7  101.57  5002.1  100.96  5058.5  114.38  5080.2  114.98
  5126.6  114.21  5164.3  113.59  5216.5   116.4  5256.5   117.2  5286.5   116.3
  5326.5   117.9  5806.5     120  6006.5   123.8  6216.5   124.2  6271.9   125.6
#Mann= 6 ,-1 , 0
  3555.4      .1       0  4928.2     .06       0  4944.6     .04       0
  5058.5     .06       0  5126.6      .1       0  6271.9     .99       0
#XS Ineff= 2 , 0
       0  4950.2  114.26 5050.34       0  114.39
Permanent Ineff=
       F       F
Bank Sta=4944.6,5058.5
XS Rating Curve= 0
Exp/Cntr=.5,.3

Type RM Length L Ch R = 1 ,6475.   ,806.3,799,787.7
BEGIN DESCRIPTION:
OAKWOOD GLEN_DS - XS 1
END DESCRIPTION:
XS GIS Cut Line= 4
        3069371.       13936864.      3068302.03     13936195.97
      3068078.56     13936002.75      3067038.76     13935473.13
#Sta/Elev= 30
  3560.4  123.71  3600.4  122.14  3830.4  120.49  3950.4  122.96  4190.4  121.96
  4220.4   120.7  4440.4  120.82  4560.4   118.4  4670.4  118.54  4730.4  114.75
  4770.4  117.29  4921.1  115.41  4931.1  116.28 4992.07  101.49 5000.71  100.72
 5057.85  114.39  5091.1  116.72    5127  116.95  5216.5  116.09  5326.5  118.98
  5366.5  117.49  5856.5  120.25  5906.5  122.07  5936.5  128.24  5956.5  124.22
  5966.5  123.88  6106.5  123.89  6146.5  128.78  6186.5  124.26  6283.5  124.99
#Mann= 5 ,-1 , 0
  3560.4      .1       0  4921.1     .06       0  4931.1     .04       0
 5057.85     .06       0    5127      .1       0
Bank Sta=4931.1,5057.85
XS Rating Curve= 0
Exp/Cntr=.3,.1

Type RM Length L Ch R = 1 ,5676.   ,105.1,107.5,107.8
BEGIN DESCRIPTION:
LOUETTA_US - XS 4
END DESCRIPTION:
XS GIS Cut Line= 4
       3069934.3      13936744.1      3068803.41     13935566.04
      3068703.02     13935498.47      3067732.97     13934842.68
#Sta/Elev= 30
  3292.5  122.32  3352.5   120.1  3412.5  121.62  3672.5  118.82  3872.5  119.73
  3922.5  118.72  4062.5  120.55  4112.5  118.61  4552.5  118.07  4582.5  116.42
  4722.5  117.38  4752.5  116.09  4862.5  116.43  4902.5  114.81  4935.6  113.94
 4954.71  111.31 4975.89  101.46 4989.07    98.7  5008.8   99.78 5027.06  102.46
  5056.6  115.77  5236.6  115.96  5276.6  114.81  5436.6  116.79  5546.6  116.27
  5636.6  118.75  5736.6  119.72  5996.6  119.08  6056.6  122.13  6217.5  122.63
#Mann= 4 ,-1 , 0
  3292.5     .09       0  4902.5     .06       0  4935.6     .04       0
  5056.6      .1       0
Bank Sta=4935.6,5056.6
XS Rating Curve= 0
Exp/Cntr=.5,.3