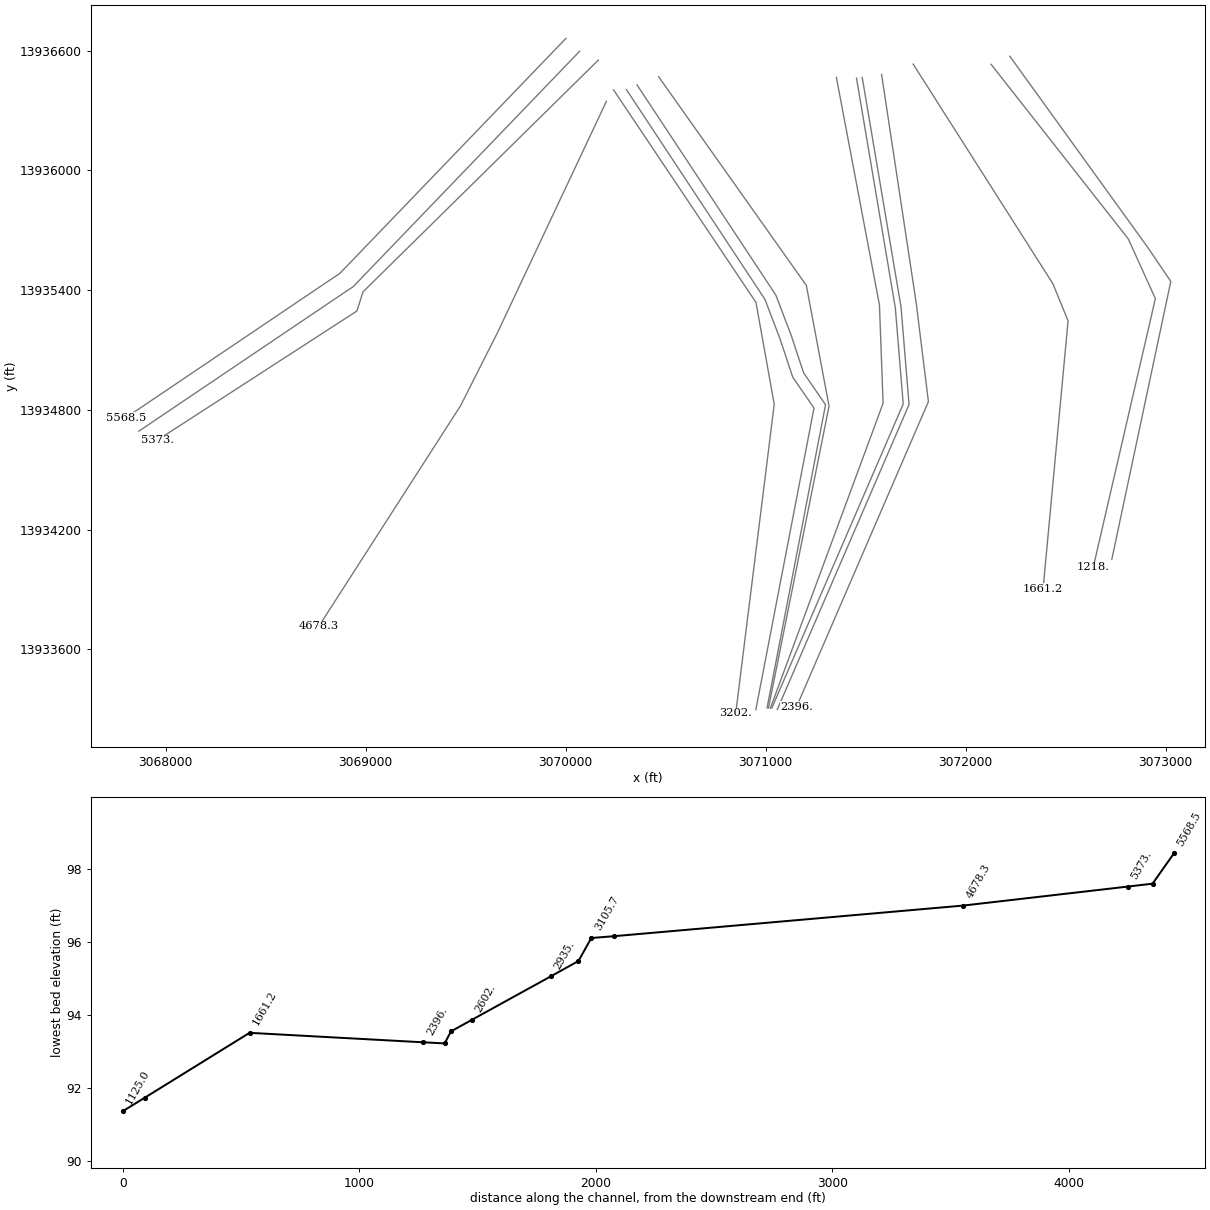
HEC-RAS study K131-02-00.prj: K131-02-00

--- K131-02-00.g01 (geometry) --- (continued)

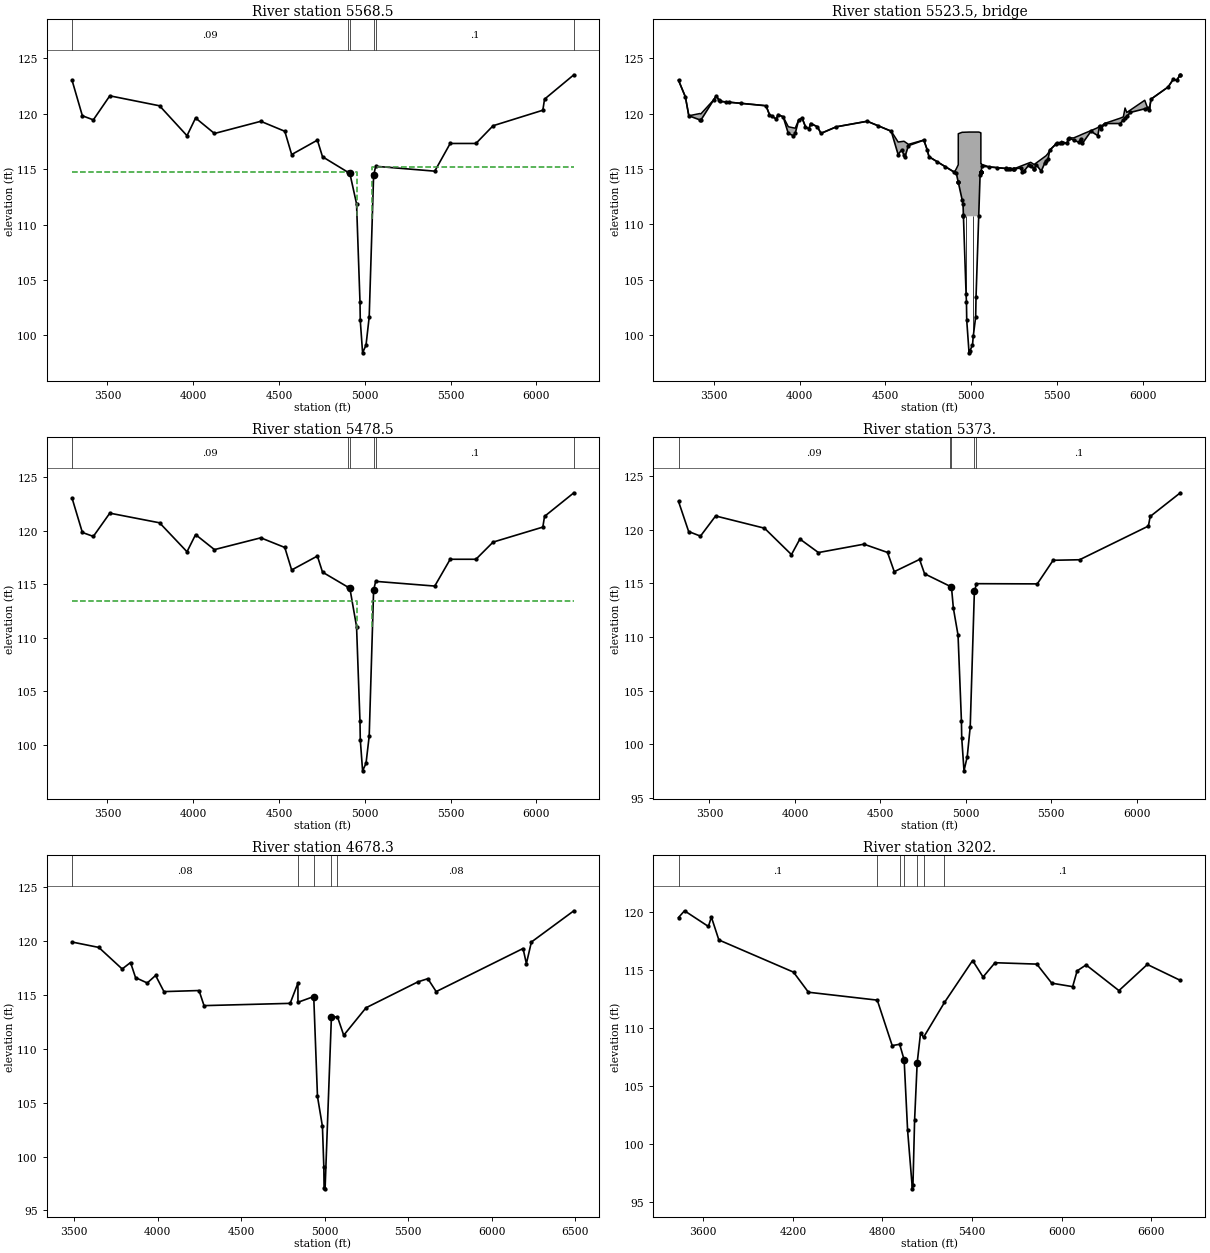
Type RM Length L Ch R = 1 ,5568.5  ,96.6,90,89
BEGIN DESCRIPTION:
Upstream Section of Bridge/Culvert/Weir
END DESCRIPTION:
XS GIS Cut Line= 4
      3070001.36     13936662.21      3068870.45      13935484.1
      3068770.06     13935416.53      3067800.01     13934760.74
#Sta/Elev= 30
    3294  123.03    3354  119.83  3417.9  119.46    3514  121.63    3804  120.73
    3964  118.03    4014  119.63    4124  118.23    4394  119.33    4534  118.43
    4574  116.33    4724  117.63  4753.9  116.13  4902.2  114.73  4913.3  114.63
  4952.3  111.88  4972.3  103.04    4974  101.35  4987.5   98.43  5007.5   99.13
    5026  101.67  5051.7  114.44  5063.7  115.27  5408.1  114.83  5498.1  117.33
  5648.1  117.33  5748.1  118.93  6038.1  120.33  6048.1  121.33    6219  123.53
#Mann= 6 ,-1 , 0
    3294     .09       0  4902.2     .06       0  4913.3     .04       0
  5051.7     .06       0  5063.7      .1       0    6219     .99       0
#XS Ineff= 2 , 0
       0 4954.71  114.71  5043.8       0  115.25
Permanent Ineff=
       F       F
Bank Sta=4913.3,5051.7
XS Rating Curve= 0
Exp/Cntr=.5,.3

Type RM Length L Ch R = 3 ,5523.5  ,,,
BEGIN DESCRIPTION:
LOUETTA
Structure ID: K131-02-00-S3
END DESCRIPTION:
Bridge Culvert--1,0,-1,-1, 0
Deck Dist Width WeirC Skew NumUp NumDn MinLoCord MaxHiCord MaxSubmerge Is_Ogee
10,70,2.6,0, 122, 122, , , .95, 0, ,,,
    3294    3334    3354  3417.9    3424  3497.9    3514  3527.9    3534  3567.9
  3587.9  3657.9    3804    3824  3837.9    3864    3874    3904    3934    3964
    3974    3994    4014    4034    4054    4064    4104    4124    4214    4394
  4457.9    4534    4574    4594  4607.9    4614    4634    4724    4744  4753.9
  4800.2  4846.9  4902.2  4913.3 4924.59  4924.7 4924.81  4947.5  4952.3 4954.51
 4954.63  4954.7  4970.2  4972.3    4974  4987.5  4992.8  5007.5  5011.9    5026
  5028.2  5043.8  5051.7 5056.16 5056.27 5056.37 5056.48 5056.59  5056.7  5063.7
  5104.8  5151.7  5201.2  5205.3  5215.3  5225.3  5245.3  5246.9  5247.1  5288.1
  5298.1  5308.1  5338.1  5346.9  5366.9  5368.1  5378.1  5408.1  5428.1  5436.9
  5448.1  5458.1  5496.9  5498.1  5516.9  5526.9  5558.1  5566.9  5568.1  5596.9
  5628.1  5638.1  5648.1  5698.1  5738.1  5748.1  5758.1  5778.1  5868.1  5886.9
  5896.9  5906.9  5928.1  6011.6  6028.1  6038.1  6048.1  6148.1  6178.1  6198.1
  6218.1    6219
     123   121.5   119.8     120  119.97  121.22  121.61  121.26  121.11  121.06
  121.03  120.93  120.71  119.91  119.77  119.51  119.91  119.71  118.81  118.71
  118.68  119.41  119.61  118.81  118.61  119.11  118.81  118.22  118.81  119.31
   118.9  118.41  117.43  117.47   117.5  117.44  117.22  117.61  116.71  116.11
  115.67  115.23  114.71  115.02  115.38  118.18  118.18  118.31  118.31  118.31
  118.31  118.31  118.32  118.32  118.32  118.33  118.33  118.33  118.33  118.33
  118.33  118.33  118.29  118.26  118.26  118.26  115.46  115.46  115.46   115.4
  115.19  115.12  115.05   115.1  115.03   115.1  114.98     115     115  115.25
  115.31  115.37  115.55   115.6   115.4  115.41  115.53  115.87   116.1   116.2
  116.41  116.71   117.3  117.31  117.31   117.5  117.31  117.75  117.81   117.8
     118  118.07  118.14  118.46  118.73  118.91  118.86  119.11  119.58   119.7
   120.5   120.1  120.32   121.2   120.5   120.3   121.3   122.4   123.1     123
   123.5   123.5
                                                                                
                                                                                
                                                                                
                                                                                
                                                                  110.79  110.79
  110.79  110.76  110.72  110.72  110.72  110.73  110.73  110.73  110.73  110.73
  110.73  110.74  114.41
                                                                                
                                                                                
                                                                                
                                                                                
                                                                                
                
    3294    3334    3354  3417.9    3424  3497.9    3514  3527.9    3534  3567.9
  3587.9  3657.9    3804    3824  3837.9    3864    3874    3904    3934    3964
    3974    3994    4014    4034    4054    4064    4104    4124    4214    4394
  4457.9    4534    4574    4594  4607.9    4614    4634    4724    4744  4753.9
  4800.2  4846.9  4902.2  4913.3 4924.59  4924.7 4924.81  4947.5  4952.3 4954.51
 4954.63  4954.7  4970.2  4972.3    4974  4987.5  4992.8  5007.5  5011.9    5026
  5028.2  5043.8  5051.7 5056.16 5056.27 5056.37 5056.48 5056.59  5056.7  5063.7
  5104.8  5151.7  5201.2  5205.3  5215.3  5225.3  5245.3  5246.9  5247.1  5288.1
  5298.1  5308.1  5338.1  5346.9  5366.9  5368.1  5378.1  5408.1  5428.1  5436.9
  5448.1  5458.1  5496.9  5498.1  5516.9  5526.9  5558.1  5566.9  5568.1  5596.9
  5628.1  5638.1  5648.1  5698.1  5738.1  5748.1  5758.1  5778.1  5868.1  5886.9
  5896.9  5906.9  5928.1  6011.6  6028.1  6038.1  6048.1  6148.1  6178.1  6198.1
  6218.1    6219
     123   121.5   119.8     120  119.97  121.22  121.61  121.26  121.11  121.06
  121.03  120.93  120.71  119.91  119.77  119.51  119.91  119.71  118.81  118.71
  118.68  119.41  119.61  118.81  118.61  119.11  118.81  118.22  118.81  119.31
   118.9  118.41  117.43  117.47   117.5  117.44  117.22  117.61  116.71  116.11
  115.67  115.23  114.71  115.02  115.38  118.18  118.18  118.31  118.31  118.31
  118.31  118.31  118.32  118.32  118.32  118.33  118.33  118.33  118.33  118.33
  118.33  118.33  118.29  118.26  118.26  118.26  115.46  115.46  115.46   115.4
  115.19  115.12  115.05   115.1  115.03   115.1  114.98     115     115  115.25
  115.31  115.37  115.55   115.6   115.4  115.41  115.53  115.87   116.1   116.2
  116.41  116.71   117.3  117.31  117.31   117.5  117.31  117.75  117.81   117.8
     118  118.07  118.14  118.46  118.73  118.91  118.86  119.11  119.58   119.7
   120.5   120.1  120.32   121.2   120.5   120.3   121.3   122.4   123.1     123
   123.5   123.5
                                                                                
                                                                                
                                                                                
                                                                                
                                                                  110.76  110.76
  110.76  110.76  110.72  110.72  110.72  110.73  110.73  110.73  110.73  110.73
  110.73  110.74  110.74
                                                                                
                                                                                
                                                                                
                                                                                
                                                                                
                
Pier Skew, UpSta & Num, DnSta & Num=  ,4970.2, 2 ,4970.2, 2 , 0 , 0 , 0 ,,
     1.3     1.3
  102.48  111.72
     1.3     1.3
  101.69  110.93
Pier Skew, UpSta & Num, DnSta & Num=  ,5011.9, 2 ,5011.9, 2 , 0 , 0 , 0 ,,
     1.3     1.3
   98.77  111.73
     1.3     1.3
   97.98  110.94
BR Coef= 1 , 1 , 1 ,1.25, 0 ,,,.8,0,2,0,
WSPro=,,,, 1 ,,,, 0 ,,,, 0 ,,,,-1 ,-1 ,-1 , 0 , 0 , 0 , 0 , 0
BR U #Sta/Elev= 122
    3294     123    3334   121.5    3354   119.8  3417.9  119.43    3424   119.4
  3497.9  121.21    3514   121.6  3527.9  121.25    3534   121.1  3567.9  121.05
  3587.9  121.02  3657.9  120.92    3804   120.7    3824   119.9  3837.9  119.76
    3864   119.5    3874   119.9    3904   119.7    3934   118.2    3964     118
    3974   118.2    3994   119.4    4014   119.6    4034   118.8    4054   118.6
    4064   119.1    4104   118.8    4124   118.2    4214   118.8    4394   119.3
  4457.9  118.89    4534   118.4    4574   116.3    4594   116.7  4607.9  116.28
    4614   116.1    4634   117.1    4724   117.6    4744   116.7  4753.9   116.1
  4800.2  115.66  4846.9  115.22  4902.2   114.7  4913.3   114.6 4924.59   113.8
  4924.7   113.8 4924.81  113.79  4947.5  112.19  4952.3  111.85 4954.51  110.84
 4954.63  110.79  4954.7  110.76  4970.2  103.69  4972.3  103.01    4974  101.32
  4987.5    98.4  4992.8   98.59  5007.5    99.1  5011.9   99.89    5026  101.64
  5028.2  103.48  5043.8  110.74  5051.7  114.41 5056.16  114.72 5056.27  114.73
 5056.37  114.73 5056.48  114.74 5056.59  114.75  5056.7  114.76  5063.7  115.24
  5104.8  115.18  5151.7  115.11  5201.2  115.04  5205.3  115.03  5215.3  115.02
  5225.3     115  5245.3  114.97  5246.9  114.97  5247.1  114.97  5288.1   115.1
  5298.1   114.7  5308.1   114.8  5338.1   115.4  5346.9  115.28  5366.9  115.02
  5368.1     115  5378.1   115.4  5408.1   114.8  5428.1   115.5  5436.9  115.68
  5448.1   115.9  5458.1   116.7  5496.9  117.28  5498.1   117.3  5516.9   117.3
  5526.9   117.3  5558.1   117.3  5566.9  117.74  5568.1   117.8  5596.9  117.61
  5628.1   117.4  5638.1   117.7  5648.1   117.3  5698.1   118.4  5738.1     118
  5748.1   118.9  5758.1   118.6  5778.1   119.1  5868.1   119.1  5886.9  119.41
  5896.9  119.58  5906.9  119.75  5928.1   120.1  6011.6  120.43  6028.1   120.5
  6038.1   120.3  6048.1   121.3  6148.1   122.4  6178.1   123.1  6198.1     123
  6218.1   123.5    6219   123.5
BR U #Mann= 5
    3294     .09  4902.2     .06  4913.3     .04  5051.7     .06  5063.7      .1
BR U Banks=4913.3,5051.7
BR D #Sta/Elev= 122
    3294  123.03    3334  121.53    3354  119.83  3417.9  119.46    3424  119.43
  3497.9  121.24    3514  121.63  3527.9  121.28    3534  121.13  3567.9  121.08
  3587.9  121.05  3657.9  120.95    3804  120.73    3824  119.93  3837.9  119.79
    3864  119.53    3874  119.93    3904  119.73    3934  118.23    3964  118.03
    3974  118.23    3994  119.43    4014  119.63    4034  118.83    4054  118.63
    4064  119.13    4104  118.83    4124  118.23    4214  118.83    4394  119.33
  4457.9  118.92    4534  118.43    4574  116.33    4594  116.73  4607.9  116.31
    4614  116.13    4634  117.13    4724  117.63    4744  116.73  4753.9  116.13
  4800.2  115.69  4846.9  115.25  4902.2  114.73  4913.3  114.63 4924.59  113.01
  4924.7  113.01 4924.81     113  4947.5   111.4  4952.3  111.06 4954.51  110.05
 4954.63     110  4954.7  109.97  4970.2   102.9  4972.3  102.22    4974  100.53
  4987.5   97.61  4992.8    97.8  5007.5   98.31  5011.9    99.1    5026  100.85
  5028.2  102.69  5043.8  109.95  5051.7  114.44 5056.16  114.75 5056.27  114.76
 5056.37  114.76 5056.48  114.77 5056.59  114.78  5056.7  114.79  5063.7  115.27
  5104.8  115.21  5151.7  115.14  5201.2  115.07  5205.3  115.06  5215.3  115.05
  5225.3  115.03  5245.3     115  5246.9     115  5247.1     115  5288.1  115.13
  5298.1  114.73  5308.1  114.83  5338.1  115.43  5346.9  115.31  5366.9  115.05
  5368.1  115.03  5378.1  115.43  5408.1  114.83  5428.1  115.53  5436.9  115.71
  5448.1  115.93  5458.1  116.73  5496.9  117.31  5498.1  117.33  5516.9  117.33
  5526.9  117.33  5558.1  117.33  5566.9  117.77  5568.1  117.83  5596.9  117.64
  5628.1  117.43  5638.1  117.73  5648.1  117.33  5698.1  118.43  5738.1  118.03
  5748.1  118.93  5758.1  118.63  5778.1  119.13  5868.1  119.13  5886.9  119.44
  5896.9  119.61  5906.9  119.78  5928.1  120.13  6011.6  120.46  6028.1  120.53
  6038.1  120.33  6048.1  121.33  6148.1  122.43  6178.1  123.13  6198.1  123.03
  6218.1  123.53    6219  123.53
BR D #Mann= 5
    3294     .09  4902.2     .06  4913.3     .04  5051.7     .06  5063.7      .1
BR D Banks=4913.3,5051.7
BC Design=,, 0 ,, 0 ,,,,,,

Type RM Length L Ch R = 1 ,5478.5  ,57.8,105.5,128.8
BEGIN DESCRIPTION:
Downstream Section of Bridge/Culvert/Weir
END DESCRIPTION:
XS GIS Cut Line= 4
      3070069.87     13936597.59      3068937.48     13935417.94
      3068835.33     13935349.19       3067865.3      13934693.4
#Sta/Elev= 30
    3294  123.03    3354  119.83  3417.9  119.46    3514  121.63    3804  120.73
    3964  118.03    4014  119.63    4124  118.23    4394  119.33    4534  118.43
    4574  116.33    4724  117.63  4753.9  116.13  4902.2  114.73  4913.3  114.63
  4952.3  111.05  4972.3  102.21    4974  100.52  4987.5    97.6  5007.5    98.3
    5026  100.84  5051.7  114.44  5063.7  115.27  5408.1  114.83  5498.1  117.33
  5648.1  117.33  5748.1  118.93  6038.1  120.33  6048.1  121.33    6219  123.53
#Mann= 6 ,-1 , 0
    3294     .09       0  4902.2     .06       0  4913.3     .04       0
  5051.7     .06       0  5063.7      .1       0    6219     .99       0
#XS Ineff= 2 , 0
       0 4952.95   113.4 5045.19       0   113.4
Permanent Ineff=
       F       F
Bank Sta=4913.3,5051.7
XS Rating Curve= 0
Exp/Cntr=.5,.3

Type RM Length L Ch R = 1 ,5373.   ,687.7,694.7,707.7
BEGIN DESCRIPTION:
LOUETTA_DS - XS 1
END DESCRIPTION:
XS GIS Cut Line= 4
      3070162.99      13936552.9      3068986.19     13935391.35
      3068956.09     13935295.82      3067958.42     13934648.71
#Sta/Elev= 30
 3319.43  122.62 3378.59  119.82 3447.61  119.39 3536.34  121.27 3822.27  120.13
 3980.02  117.67 4029.31  119.12 4137.77  117.86 4403.97  118.64 4542.01  117.87
 4581.44  116.08 4729.34  117.22 4758.82  115.88 4905.03  114.74 4915.98  114.66
 4927.14  112.68 4954.54  110.16 4974.32  102.17    4976  100.61 4989.35   97.52
 5008.26   98.84 5025.76  101.63 5050.07  114.24 5062.45  114.96 5417.91  114.94
 5510.79  117.14 5665.61  117.19 6068.13  120.33 6078.45  121.22 6254.83  123.43
#Mann= 5 ,-1 , 0
 3319.43     .09       0 4905.03     .06       0 4915.98     .04       0
 5050.07     .06       0 5062.45      .1       0
Bank Sta=4915.98,5050.07
XS Rating Curve= 0
Exp/Cntr=.3,.1

Type RM Length L Ch R = 1 ,4678.3  ,1414.1,1476.3,1508.4
BEGIN DESCRIPTION:
Cross Section K131-02-00-X4
END DESCRIPTION:
XS GIS Cut Line= 4
      3070203.45     13936346.16      3069660.09     13935189.62
      3069474.76     13934821.84      3068765.42     13933715.45
#Sta/Elev= 30
  3486.9   119.9  3646.9   119.4  3786.9   117.4  3836.9     118  3866.9   116.6
  3936.9   116.1  3986.9   116.8  4036.9   115.3  4246.9   115.4  4276.9     114
  4792.3  114.21    4839  116.09  4839.2  114.31  4933.6  114.84    4956  105.57
  4985.7  102.79  4994.1   98.98  4995.6   97.04  5001.5      97  5039.3  112.91
  5075.4  112.97  5113.1  111.25  5246.6   113.8  5556.6   116.2  5616.6   116.5
  5666.6   115.3  6186.6   119.3  6206.6   117.9  6236.6   119.9  6490.8   122.8
#Mann= 5 ,-1 , 0
  3486.9     .08       0  4839.2     .06       0  4933.6     .04       0
  5039.3     .06       0  5075.4     .08       0
Bank Sta=4933.6,5039.3
XS Rating Curve= 0
Exp/Cntr=.3,.1

Type RM Length L Ch R = 1 ,3202.   ,85.2,96.3,105
BEGIN DESCRIPTION:
SIR WILLIAM_US - XS 4
END DESCRIPTION:
XS GIS Cut Line= 4
      3070239.54      13936403.7      3070951.59     13935338.82
      3071042.96     13934828.42      3070850.37      13933279.2
#Sta/Elev= 30
  3434.1  119.51  3474.1  120.09  3634.1  118.74  3654.1  119.55  3704.1  117.58
  4204.1  114.81  4304.1  113.08  4765.1   112.4  4865.1  108.49  4915.1   108.6
  4945.1  107.26 4968.23   101.2 5000.19   96.16 5004.18    96.5 5015.07  102.06
 5032.33  106.99  5055.1  109.58  5075.1   109.2  5215.1   112.2  5403.7  115.81
  5473.7  114.39  5553.7  115.62  5833.7   115.5  5933.7  113.86  6073.7  113.56
  6103.7  114.92  6163.7  115.43  6383.7  113.22  6573.7  115.47  6794.8   114.1
#Mann= 7 ,-1 , 0
  3434.1      .1       0  4765.1     .08       0  4915.1     .06       0
  4945.1     .04       0 5032.33     .06       0  5075.1     .08       0
  5215.1      .1       0
Bank Sta=4945.1,5032.33
XS Rating Curve= 0
Exp/Cntr=.5,.3

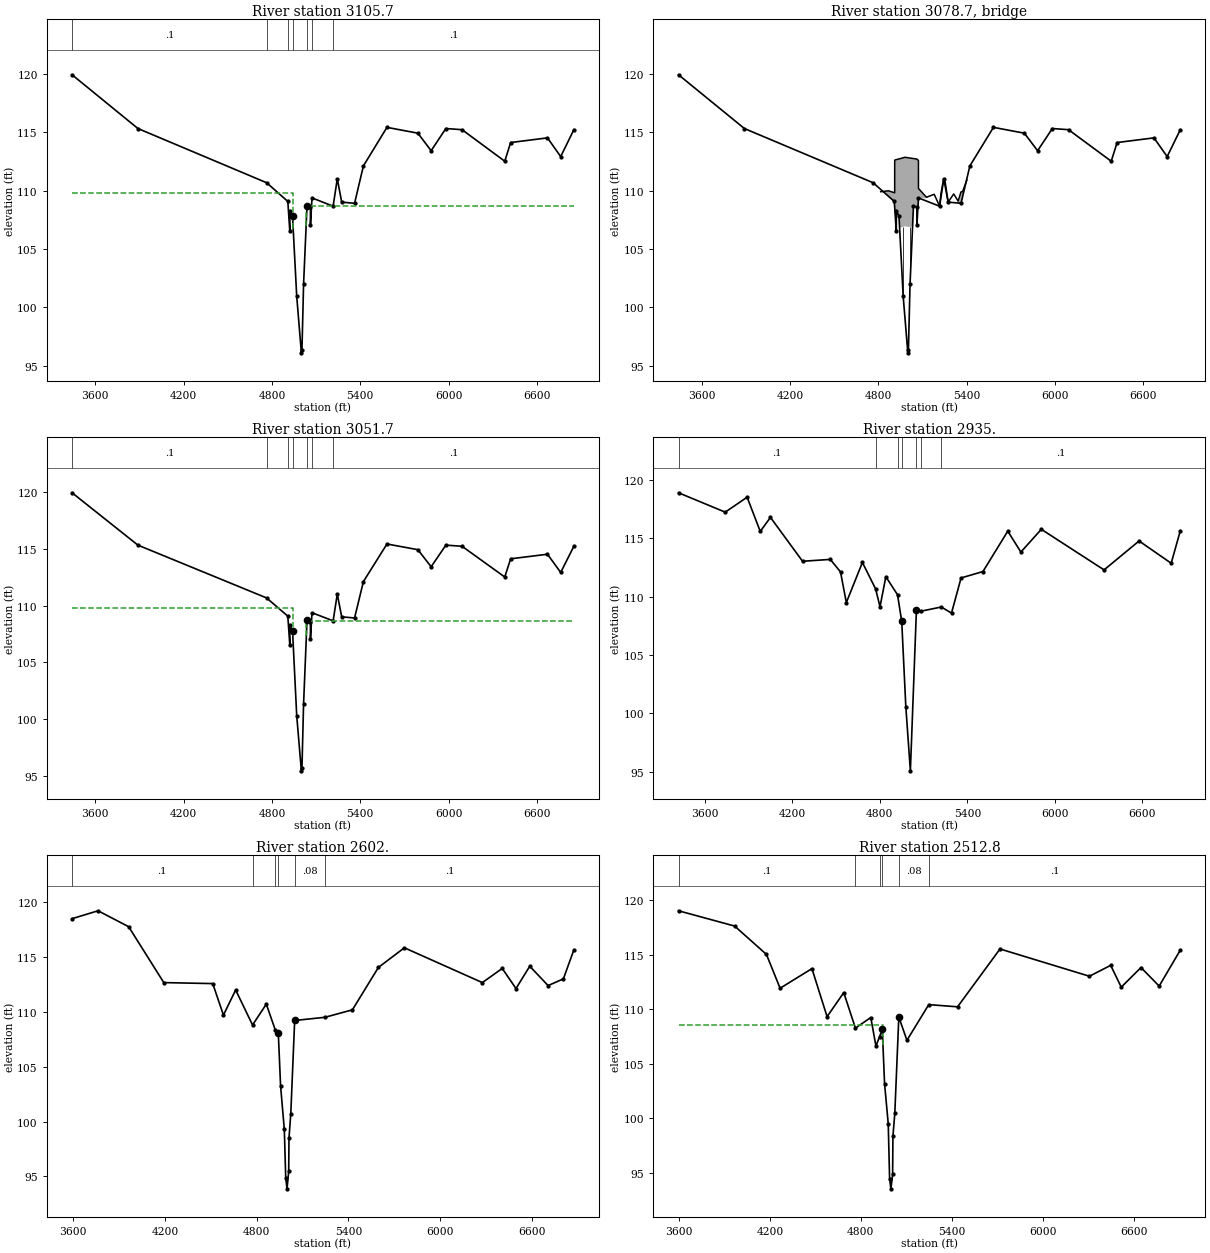
Type RM Length L Ch R = 1 ,3105.7  ,53,54,59.2
BEGIN DESCRIPTION:
Upstream Section of Bridge/Culvert/Weir
END DESCRIPTION:
XS GIS Cut Line= 6
      3070303.48      13936405.6      3070996.69     13935353.75
      3071071.98     13935155.87      3071135.69     13934963.77
      3071241.87     13934809.33      3070950.93     13933297.82
#Sta/Elev= 30
  3442.8  119.91    3890  115.31  4764.1  110.67  4908.1  109.07  4921.7   106.5
  4922.2  108.28  4940.1  107.79  4968.4  100.97  5000.1   96.11  5004.1   96.36
    5015  101.96  5038.4  108.69  5061.4  108.57  5061.7  107.04 5072.31  109.37
  5215.8  108.66    5244  111.01    5274  109.01  5361.4  108.91  5421.4  112.11
  5581.4  115.41  5791.4  114.91  5881.4  113.41  5981.4  115.31  6091.4  115.21
  6381.4  112.51  6421.4  114.11  6671.4  114.51  6761.4  112.91  6850.7  115.21
#Mann= 7 ,-1 , 0
  3442.8      .1       0  4764.1     .08       0  4908.1     .06       0
  4940.1     .04       0  5038.4     .06       0 5072.31     .08       0
  5215.8      .1       0
#XS Ineff= 2 , 0
       0 4944.45  109.81 5032.48       0  108.66
Permanent Ineff=
       F       F
Bank Sta=4940.1,5038.4
XS Rating Curve= 0
Exp/Cntr=.5,.3

Type RM Length L Ch R = 3 ,3078.7  ,,,
BEGIN DESCRIPTION:
SIR WILLIAM
Structure ID: K131-02-00-S2
END DESCRIPTION:
Bridge Culvert--1,0,-1,-1, 0
Deck Dist Width WeirC Skew NumUp NumDn MinLoCord MaxHiCord MaxSubmerge Is_Ogee
10,34,2.6,0, 31, 28, , , .95, 0, ,,,
  4815.7  4868.4  4908.1 4910.69  4910.8 4910.91  4921.7  4922.2  4940.1 4944.43
  4980.3  5032.5  5038.4  5061.4  5061.7  5071.1  5072.2 5072.31  5126.6  5179.1
  5215.8  5224.9    5244    5254    5274  5311.6  5331.4  5341.4  5361.4  5371.6
  5401.4
   109.9  109.98  109.82  109.81  112.21   112.6  112.65  112.65  112.71  112.72
  112.85  112.75  112.74   112.7  112.69  112.59  112.58  110.18  109.43  109.68
  108.66  109.74  111.01  110.71  109.01  109.71  109.31   109.1  109.89   109.9
  110.91
  109.89  109.46  109.06  108.57  108.55  108.53  106.49  108.27  107.78   106.8
  106.95  106.82  108.68  108.56  107.03  109.36  109.36  109.36  109.34  109.67
  108.65  109.73     111   110.7     109   109.7   109.3   108.7   108.9  109.41
   110.9
  4815.7  4868.4  4908.1 4910.69  4910.8 4910.91  4921.7  4922.2  4923.7  4980.3
  5061.4  5061.7  5071.1  5072.2 5072.31  5126.6  5179.1  5215.8  5224.9    5244
    5254    5274  5311.6  5331.4  5341.4  5361.4  5371.6  5401.4
   109.9  109.98  109.82  109.81  112.21   112.6  112.65  112.65  112.65  112.85
   112.7  112.69  112.59  112.58  110.18  109.43  109.68  108.66  109.74  111.01
  110.71  109.01  109.71  109.31   109.1  109.89   109.9  110.91
  109.89  109.46  109.06  108.57  108.55  108.53  106.49  108.27  106.82  106.95
  106.85  107.03  109.36  109.36  109.36  109.34  109.67  108.65  109.73     111
   110.7     109   109.7   109.3   108.7   108.9  109.41   110.9
Pier Skew, UpSta & Num, DnSta & Num=  ,4968.4, 2 ,4968.4, 2 , 0 , 0 , 0 ,,
     1.2     1.2
   99.84  107.91
     1.2     1.2
   99.26  107.33
Pier Skew, UpSta & Num, DnSta & Num=  ,5015, 2 ,5015, 2 , 0 , 0 , 0 ,,
     1.2     1.2
  100.68  107.88
     1.2     1.2
   100.1   107.3
BR Coef= 1 , 1 , 1 ,1.25, 0 ,,,.8,0,2,0,
WSPro=,,,, 1 ,,,, 0 ,,,, 0 ,,,,-1 ,-1 ,-1 , 0 , 0 , 0 , 0 , 0
BC Design=,, 0 ,, 0 ,,,,,,

Type RM Length L Ch R = 1 ,3051.7  ,121.2,116.7,102.6
BEGIN DESCRIPTION:
Downstream Section of Bridge/Culvert/Weir
END DESCRIPTION:
XS GIS Cut Line= 6
      3070356.71     13936428.94      3071051.13     13935375.25
      3071127.44      13935174.7      3071189.92     13934985.66
      3071299.62      13934826.1       3071007.1     13933306.37
#Sta/Elev= 30
  3442.8  119.91    3890  115.31  4764.1  110.67  4908.1  109.07  4921.7   106.5
  4922.2  108.28  4940.1  107.79  4968.4  100.34  5000.1   95.48  5004.1   95.73
    5015  101.33  5038.4  108.69  5061.4  108.57  5061.7  107.04 5072.31  109.37
  5215.8  108.66    5244  111.01    5274  109.01  5361.4  108.91  5421.4  112.11
  5581.4  115.41  5791.4  114.91  5881.4  113.41  5981.4  115.31  6091.4  115.21
  6381.4  112.51  6421.4  114.11  6671.4  114.51  6761.4  112.91  6850.7  115.21
#Mann= 7 ,-1 , 0
  3442.8      .1       0  4764.1     .08       0  4908.1     .06       0
  4940.1     .04       0  5038.4     .06       0 5072.31     .08       0
  5215.8      .1       0
#XS Ineff= 2 , 0
       0 4942.59  109.81 5034.04       0  108.66
Permanent Ineff=
       F       F
Bank Sta=4940.1,5038.4
XS Rating Curve= 0
Exp/Cntr=.5,.3

Type RM Length L Ch R = 1 ,2935.   ,337.8,333,320.2
BEGIN DESCRIPTION:
SIR WILLIAM_DS - XS 1
END DESCRIPTION:
XS GIS Cut Line= 4
       3070464.7      13936469.9      3071203.64     13935423.89
      3071317.07     13934818.96      3071014.16     13933306.34
#Sta/Elev= 30
  3420.9  118.89  3740.9  117.23  3890.9  118.51  3980.9  115.58  4050.9  116.78
  4270.9  113.02  4460.9  113.18  4530.9  112.11  4570.9  109.48  4680.9  112.92
  4771.6  110.65  4801.6  109.12  4841.6   111.7  4921.6  110.15 4950.47  107.87
 4978.42  100.57 5009.73   95.06 5051.08  108.82  5081.6  108.74  5221.6   109.1
  5291.6  108.58  5357.1  111.59  5507.1  112.14  5677.1   115.6  5767.1  113.81
  5907.1  115.76  6337.1  112.28  6577.1  114.76  6797.1  112.85  6859.7  115.64
#Mann= 7 ,-1 , 0
  3420.9      .1       0  4771.6     .08       0  4921.6     .06       0
 4950.47     .04       0 5051.08     .06       0  5081.6     .08       0
  5221.6      .1       0
Bank Sta=4950.47,5051.08
XS Rating Curve= 0
Exp/Cntr=.3,.1

Type RM Length L Ch R = 1 ,2602.   ,84.2,89.2,93.5
BEGIN DESCRIPTION:
FOOT BRIDGE_US - XS 4
END DESCRIPTION:
XS GIS Cut Line= 4
      3071353.83      13936466.4      3071569.12     13935326.22
      3071587.44     13934833.45       3071023.8     13933305.54
#Sta/Elev= 30
  3592.8  118.47  3762.8  119.19  3962.8  117.74  4192.8  112.65  4512.8  112.56
  4582.8  109.69  4662.8  111.98  4773.2  108.79  4863.2  110.69  4923.2  108.29
 4941.52   108.1 4956.66  103.23 4981.01   99.28  4990.2   94.88 4998.68   93.87
 5009.76   95.47 5011.48   98.47 5023.43  100.73 5048.75   109.2  5246.3  109.49
  5426.3  110.17  5596.3  114.03  5766.3  115.82  6276.3  112.65  6406.3  113.94
  6496.3  112.11  6586.3  114.14  6706.3  112.38  6806.3  112.99  6874.8  115.63
#Mann= 6 ,-1 , 0
  3592.8      .1       0  4773.2     .08       0  4923.2     .06       0
 4941.52     .04       0 5048.75     .08       0  5246.3      .1       0
Bank Sta=4941.52,5048.75
XS Rating Curve= 0
Exp/Cntr=.5,.3

Type RM Length L Ch R = 1 ,2512.8  ,29.2,27,26
BEGIN DESCRIPTION:
Upstream Section of Bridge/Culvert/Weir
END DESCRIPTION:
XS GIS Cut Line= 4
       3071454.4     13936462.71      3071648.42     13935312.37
        3071688.     13934829.73      3071030.89     13933305.73
#Sta/Elev= 30
  3597.5  119.03  3967.5  117.63  4177.5  115.03  4267.5  111.93  4477.5  113.73
  4577.5  109.33  4687.5  111.53  4764.5  108.28  4865.9  109.25  4899.9  106.63
  4923.8   107.5  4941.8  108.16  4956.8  103.17  4980.9   99.53    4990   94.49
  4998.4   93.55    5010   94.87  5011.8   98.35  5024.3  100.46  5050.8   109.3
  5104.3  107.16  5248.4  110.43  5438.4  110.23  5718.4  115.53  6308.4  113.03
  6448.4  114.03  6518.4  112.03  6648.4  113.83  6768.4  112.13    6908  115.43
#Mann= 6 ,-1 , 0
  3597.5      .1       0  4764.5     .08       0  4923.8     .06       0
  4941.8     .04       0  5050.8     .08       0  5248.4      .1       0
#XS Ineff= 2 , 0
       0 4946.08  108.55 5047.37       0  107.89
Permanent Ineff=
       F       F
Bank Sta=4941.8,5050.8
XS Rating Curve= 0
Exp/Cntr=.5,.3

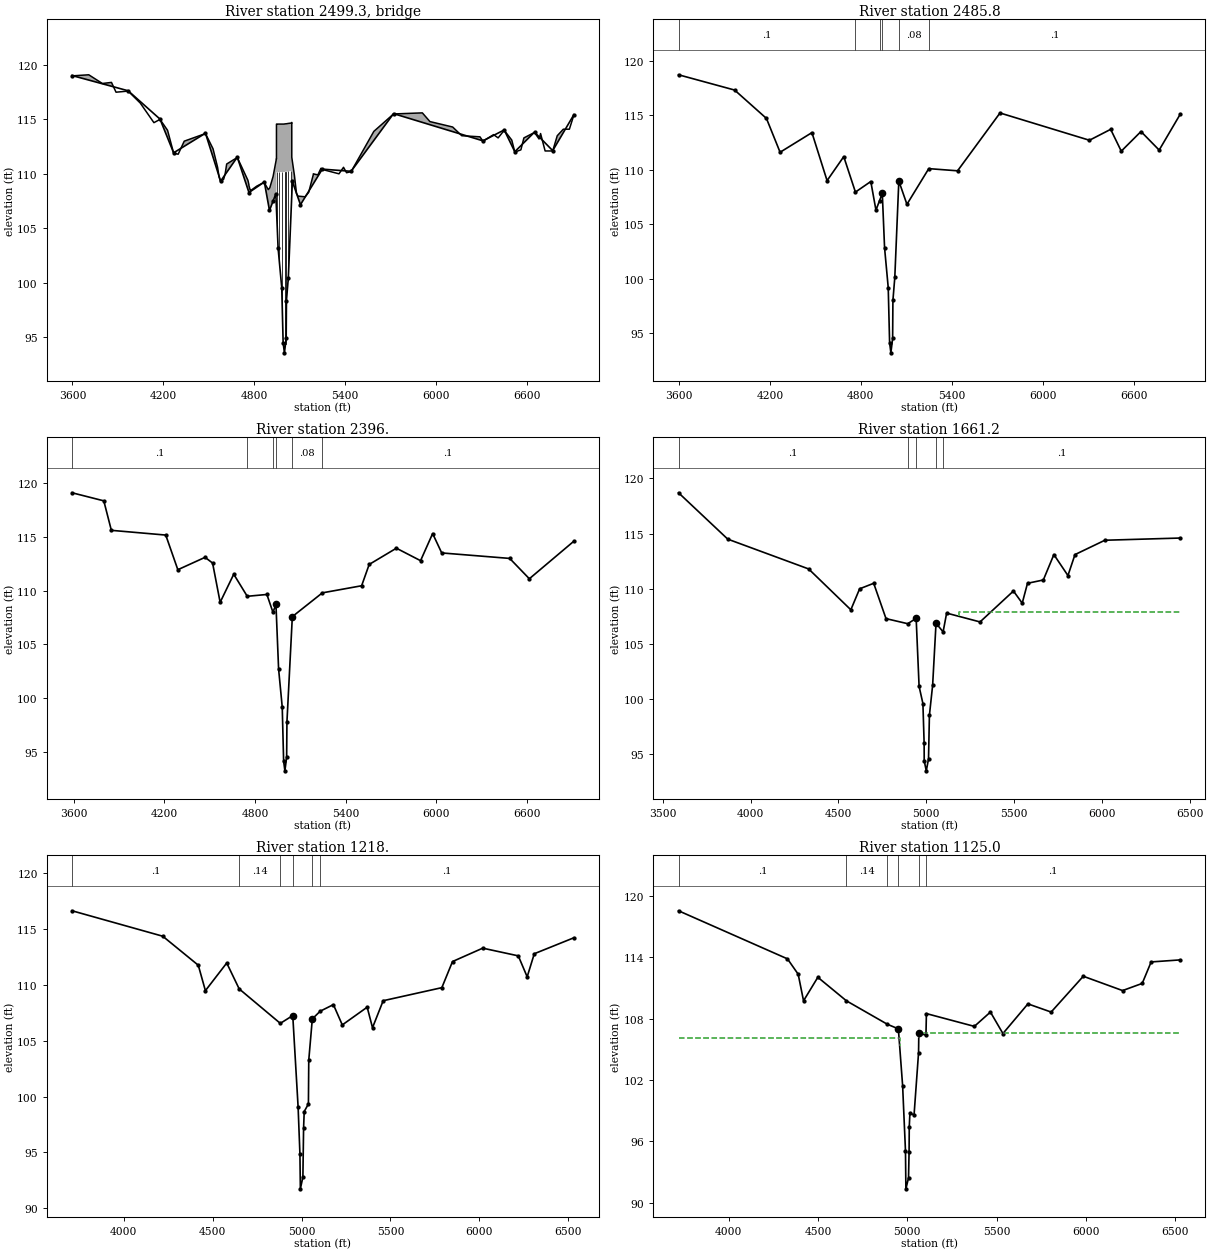
Type RM Length L Ch R = 3 ,2499.3  ,,,
BEGIN DESCRIPTION:
FOOT BRIDGE 550' DS OF SIR WILLIAM
Structure ID: K131-02-00-S1A
END DESCRIPTION:
Bridge Culvert--1,0,-1,-1, 0
Deck Dist Width WeirC Skew NumUp NumDn MinLoCord MaxHiCord MaxSubmerge Is_Ogee
10,7,2.6,0, 108, 47, , , .95, 0, ,,,
  3597.5  3707.5  3797.5  3857.5  3887.5  3967.5  4047.5  4137.5  4177.5  4227.5
  4267.5  4297.5  4337.5  4477.5  4527.5  4557.5  4567.5  4577.5  4597.5  4607.5
  4617.5  4687.5  4726.4  4756.4  4757.5  4764.1  4764.5  4772.8  4775.9  4815.1
  4823.3  4865.9  4870.6  4891.9  4899.9    4902  4923.8  4941.8  4945.6 4945.71
 4945.79  4945.9    4946  4946.1 4946.21  4956.8  4980.9  4987.6  4989.7    4990
  4995.5  4998.4    5010  5010.2  5011.1  5011.8  5024.3  5046.7  5046.8 5046.86
 5046.97 5047.08 5047.19  5047.3  5050.8  5064.5    5078  5087.8  5104.3  5134.3
  5152.9  5158.6    5182  5188.6  5189.1  5203.1  5219.1  5239.1  5240.4  5248.4
  5358.4  5388.4  5408.4  5438.4  5588.4  5718.4  5908.4  5958.4  6108.4  6168.4
  6288.4  6308.4  6378.4  6408.4  6448.4  6498.4  6518.4  6558.4  6578.4  6648.4
  6678.4  6688.4  6718.4  6768.4  6798.4  6838.4  6878.4    6908
     119   119.1   118.3   118.4   117.5   117.6   116.5   114.7     115     114
   111.9   111.8     113   113.7   112.3   110.6   109.7   109.3   109.5     110
   110.9   111.5  110.34  109.44  109.41  109.01   108.9   108.5  108.46  108.86
  108.92  109.23  109.07  108.55  108.68  108.72  109.76   111.1  111.38  111.37
  111.37  111.37  114.57  114.57  114.57  114.57  114.57  114.57  114.57  114.57
  114.57  114.58   114.6   114.6   114.6   114.6  114.63  114.67  114.67  114.72
  114.72  111.52  111.51   111.5  111.16  109.85  108.22  107.95  107.93  107.89
   108.2   108.3  109.55   109.9     110  109.95   109.9   110.5   110.5   110.4
     110   110.6   110.1   110.2   113.9   115.5   115.6   114.8   114.3   113.5
   113.4     113   113.6   113.3     114   113.1     112   112.2   113.3   113.8
   113.2   113.7   112.1   112.1   113.5   114.1   114.1   115.4
                                                                                
                                                                                
                                                                                
                                                                  106.86  106.82
  106.79  106.76  106.72  110.16  110.16  110.16  110.16  110.16  110.16  110.16
  110.16  110.17  110.19  110.19  110.19  110.19  110.22  110.26
                                                                                
                                                                                
                                                                                
                                                                                
                                                                
  4891.9  4899.9    4902  4923.8  4941.8  4945.6 4945.71 4945.79  4945.9    4946
  4946.1 4946.21  4956.8  4980.9  4987.6  4989.7    4990  4995.5  4998.4    5010
  5010.2  5011.1  5011.8  5024.3  5046.7  5046.8 5046.86 5046.97 5047.08 5047.19
  5047.3  5050.8  5064.5    5078  5087.8  5104.3  5134.3  5152.9  5158.6    5182
  5188.6  5189.1  5203.1  5219.1  5239.1  5240.4  5248.4
  108.06  108.68  108.72  109.76   111.1  111.38  111.37  111.37  111.37  114.57
  114.57  114.57  114.57  114.57  114.57  114.57  114.57  114.57  114.58   114.6
   114.6   114.6   114.6  114.63  114.67  114.67  114.72  114.72  111.52  111.51
   111.5  111.16  109.85  108.22  107.95  107.93  107.89   108.2   108.3  109.55
   109.9     110  109.95   109.9   110.5   110.5   110.1
                                                             106     106  106.43
  110.16  110.16  110.16  110.16  110.16  110.16  110.16  110.16  110.17  110.19
  110.19  110.19  110.19  110.22  110.26
                                                                                
                                                        
Pier Skew, UpSta & Num, DnSta & Num=  ,4950.1, 2 ,4950.1, 2 , 0 , 0 , 0 ,,
       1       1
  104.19  111.16
       1       1
   103.9  110.87
Pier Skew, UpSta & Num, DnSta & Num=  ,4964.5, 2 ,4964.5, 2 , 0 , 0 , 0 ,,
       1       1
  100.89  111.16
       1       1
   100.6  110.87
Pier Skew, UpSta & Num, DnSta & Num=  ,4984.9, 2 ,4984.9, 2 , 0 , 0 , 0 ,,
       1       1
   96.76  111.16
       1       1
   96.47  110.87
Pier Skew, UpSta & Num, DnSta & Num=  ,5005.3, 2 ,5005.3, 2 , 0 , 0 , 0 ,,
       1       1
   93.24  111.18
       1       1
   92.95  110.89
Pier Skew, UpSta & Num, DnSta & Num=  ,5022.5, 2 ,5022.5, 2 , 0 , 0 , 0 ,,
       1       1
   99.03  111.22
       1       1
   98.74  110.93
Pier Skew, UpSta & Num, DnSta & Num=  ,5043.1, 2 ,5043.1, 2 , 0 , 0 , 0 ,,
       1       1
  105.52  111.25
       1       1
  105.23  110.96
BR Coef= 1 , 1 , 1 ,1.25, 0 ,,,.8,0,2,0,
WSPro=,,,, 1 ,,,, 0 ,,,, 0 ,,,,-1 ,-1 ,-1 , 0 , 0 , 0 , 0 , 0
BC Design=,, 0 ,, 0 ,,,,,,

Type RM Length L Ch R = 1 ,2485.8  ,85.6,89.8,93.2
BEGIN DESCRIPTION:
Downstream Section of Bridge/Culvert/Weir
END DESCRIPTION:
XS GIS Cut Line= 4
      3071482.96     13936466.44      3071677.13     13935315.26
      3071717.19     13934826.79       3071058.1     13933298.21
#Sta/Elev= 30
  3597.5   118.7  3967.5   117.3  4177.5   114.7  4267.5   111.6  4477.5   113.4
  4577.5     109  4687.5   111.2  4764.5  107.95  4865.9  108.92  4899.9   106.3
  4923.8  107.17  4941.8  107.83  4956.8  102.84  4980.9    99.2    4990   94.16
  4998.4   93.22    5010   94.54  5011.8   98.02  5024.3  100.13  5050.8  108.97
  5104.3  106.83  5248.4   110.1  5438.4   109.9  5718.4   115.2  6308.4   112.7
  6448.4   113.7  6518.4   111.7  6648.4   113.5  6768.4   111.8    6908   115.1
#Mann= 6 ,-1 , 0
  3597.5      .1       0  4764.5     .08       0  4923.8     .06       0
  4941.8     .04       0  5050.8     .08       0  5248.4      .1       0
#XS Ineff= 2 , 0
       0    4946  106.31 5047.53       0  106.84
Permanent Ineff=
       F       F
Bank Sta=4941.8,5050.8
XS Rating Curve= 0
Exp/Cntr=.5,.3

Type RM Length L Ch R = 1 ,2396.   ,687.9,734.8,753.5
BEGIN DESCRIPTION:
FOOT BRIDGE_DS - XS 1
END DESCRIPTION:
XS GIS Cut Line= 4
       3071579.8       13936481.      3071753.14     13935334.99
      3071814.02     13934841.69      3071154.94     13933313.11
#Sta/Elev= 30
    3590  119.09    3800  118.34    3850   115.6    4210  115.16    4290  111.94
    4470  113.09    4520  112.56    4570  108.91    4660  111.52  4749.4  109.47
  4879.4  109.64  4919.4  107.99  4939.4  108.71 4956.85  102.72 4980.99   99.17
 4990.11   94.16 4998.52   93.25 5010.19   94.54 5012.01   97.78 5047.73  107.58
  5246.4  109.79  5506.4  110.45  5556.4  112.43  5736.4  113.94  5896.4  112.78
  5976.4   115.3  6036.4   113.5  6486.4  112.99  6616.4   111.1    6911  114.59
#Mann= 6 ,-1 , 0
    3590      .1       0  4749.4     .08       0  4919.4     .06       0
  4939.4     .04       0 5047.73     .08       0  5246.4      .1       0
Bank Sta=4939.4,5047.73
XS Rating Curve= 0
Exp/Cntr=.3,.1

Type RM Length L Ch R = 1 ,1661.2  ,448.9,443.2,440
BEGIN DESCRIPTION:
Cross Section K131-02-00-X03
END DESCRIPTION:
XS GIS Cut Line= 4
      3071737.57     13936533.31      3072436.26     13935432.87
      3072512.51     13935246.57      3072387.48     13933903.14
#Sta/Elev= 30
  3590.5   118.7  3870.5   114.5  4330.5   111.8  4570.5   108.1  4620.5     110
  4700.5   110.5  4770.5   107.3  4893.9  106.84    4942  107.32  4958.7  101.16
  4980.4   99.61  4987.4      96  4987.8   94.43  4999.5   93.51  5012.3   94.58
  5017.4   98.55  5035.7  101.26    5055  106.88  5095.3   106.1  5115.3   107.8
  5305.3     107  5495.3   109.8  5545.3   108.7  5575.3   110.5  5665.3   110.8
  5725.3   113.1  5805.3   111.2  5845.3   113.1  6015.3   114.4  6444.5   114.6
#Mann= 5 ,-1 , 0
  3590.5      .1       0  4893.9     .06       0    4942     .04       0
    5055     .06       0  5095.3      .1       0
#XS Ineff= 2 , 0
                         5185.36           107.9
Permanent Ineff=
       F       F
Bank Sta=4942,5055
XS Rating Curve= 0
Exp/Cntr=.3,.1

Type RM Length L Ch R = 1 ,1218.   ,70.6,93,106.2
BEGIN DESCRIPTION:
PIPE-S1_US - XS 4
END DESCRIPTION:
XS GIS Cut Line= 4
       3072127.8      13936531.6      3072813.63     13935657.04
      3072949.11     13935357.73      3072638.18     13934010.57
#Sta/Elev= 30
  3709.3  116.65  4219.3  114.37  4419.3  111.77  4459.3  109.49  4579.3  111.97
  4649.3  109.65  4880.7  106.56  4950.7  107.26  4980.7   99.09 4991.03   94.85
 4993.47   91.73 5007.67   92.78 5011.61   97.19 5015.16   98.66 5038.79   99.34
  5040.7  103.26  5060.7  106.96    5105  107.65  5179.3  108.24  5229.3  106.42
  5369.3  108.01  5399.3  106.17  5459.3  108.59  5789.3  109.76  5849.3   112.1
  6019.3   113.3  6219.3  112.61  6269.3  110.73  6309.3   112.8  6531.9  114.23
#Mann= 6 ,-1 , 0
  3709.3      .1       0  4649.3     .14       0  4880.7     .06       0
  4950.7     .04       0  5060.7     .06       0    5105      .1       0
Bank Sta=4950.7,5060.7
XS Rating Curve= 0
Exp/Cntr=.5,.3

Type RM Length L Ch R = 1 ,1125.0  ,21.3,21,20.7
BEGIN DESCRIPTION:
Upstream Section of Bridge/Culvert/Weir
END DESCRIPTION:
XS GIS Cut Line= 4
      3072220.96     13936572.65      3072911.34     13935613.94
      3073026.21     13935444.04       3072731.3     13934051.54
#Sta/Elev= 30
  3719.1  118.54  4329.1  113.84  4389.1  112.34  4419.1  109.74  4499.1  112.04
  4659.1  109.74  4889.1  107.44 4950.11     107 4973.91  101.45 4989.91   95.08
 4992.21   91.36 5007.01   92.43 5010.11      95 5011.11   97.43 5014.81   98.77
 5037.91   98.57 5063.21  104.68 5064.61  106.59 5104.61  106.38 5107.11  108.49
  5375.6  107.24  5465.6  108.64  5535.6  106.54  5675.6  109.44  5805.6  108.64
  5985.6  112.14  6205.6  110.74  6315.6  111.44  6365.6  113.54    6529  113.74
#Mann= 6 ,-1 , 0
  3719.1      .1       0  4659.1     .14       0  4889.1     .06       0
 4950.11     .04       0 5064.61     .06       0 5104.61      .1       0
#XS Ineff= 2 , 0
       0 4957.31  106.13 5064.27       0  106.56
Permanent Ineff=
       F       F
Bank Sta=4950.11,5064.61
XS Rating Curve= 0
Exp/Cntr=.5,.3