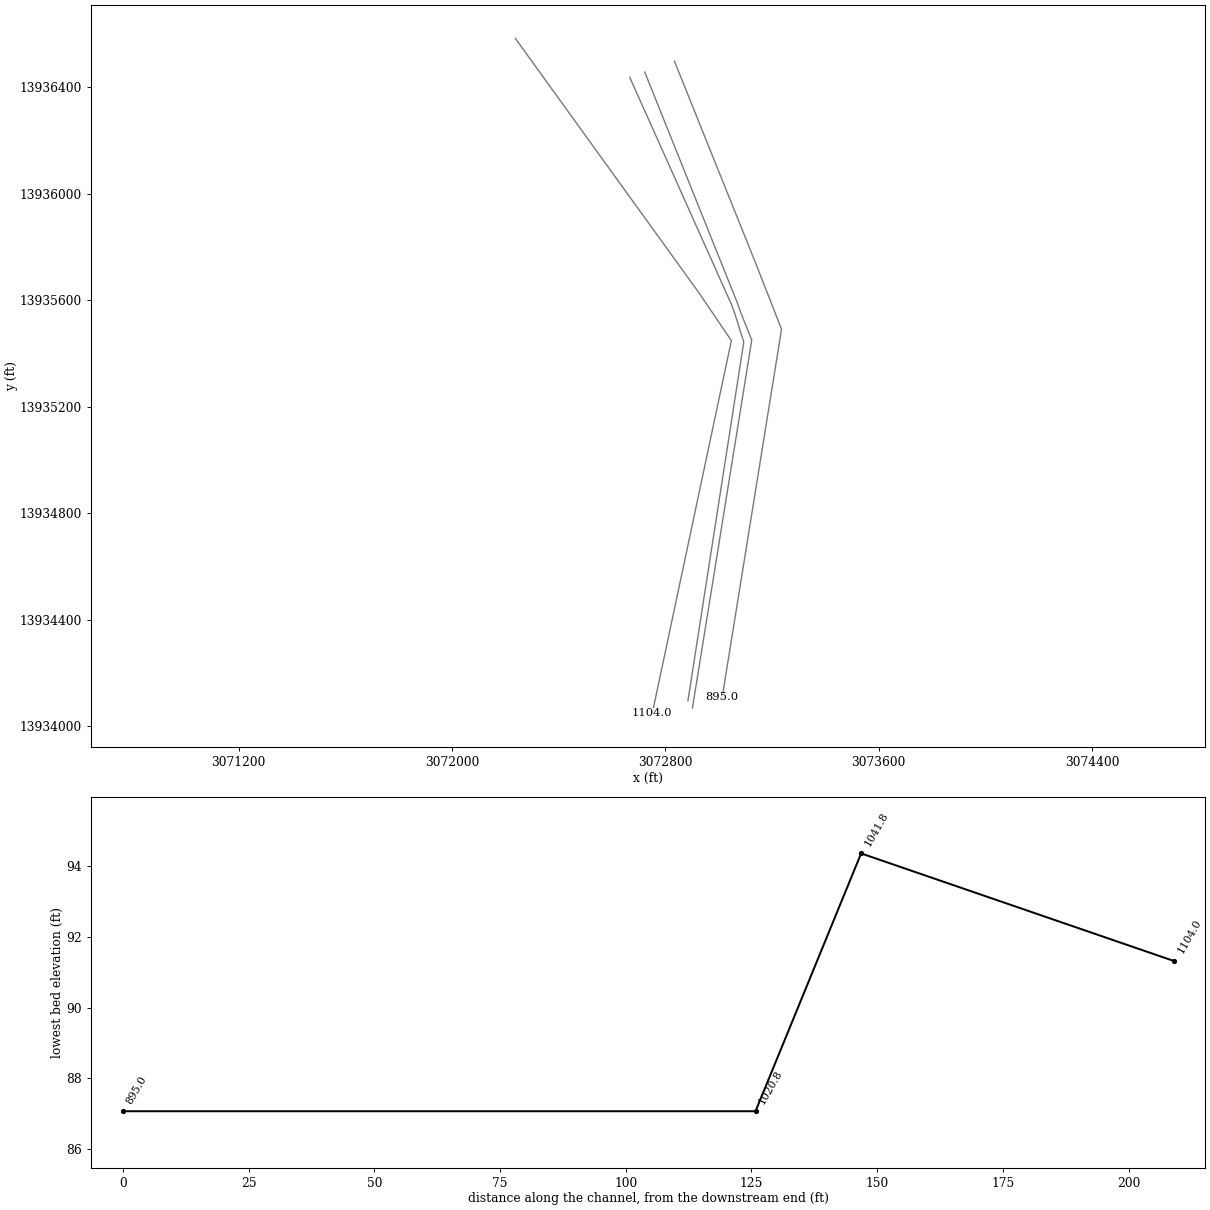
HEC-RAS study K131-02-00.prj: K131-02-00

--- K131-02-00.g01 (geometry) --- (continued)

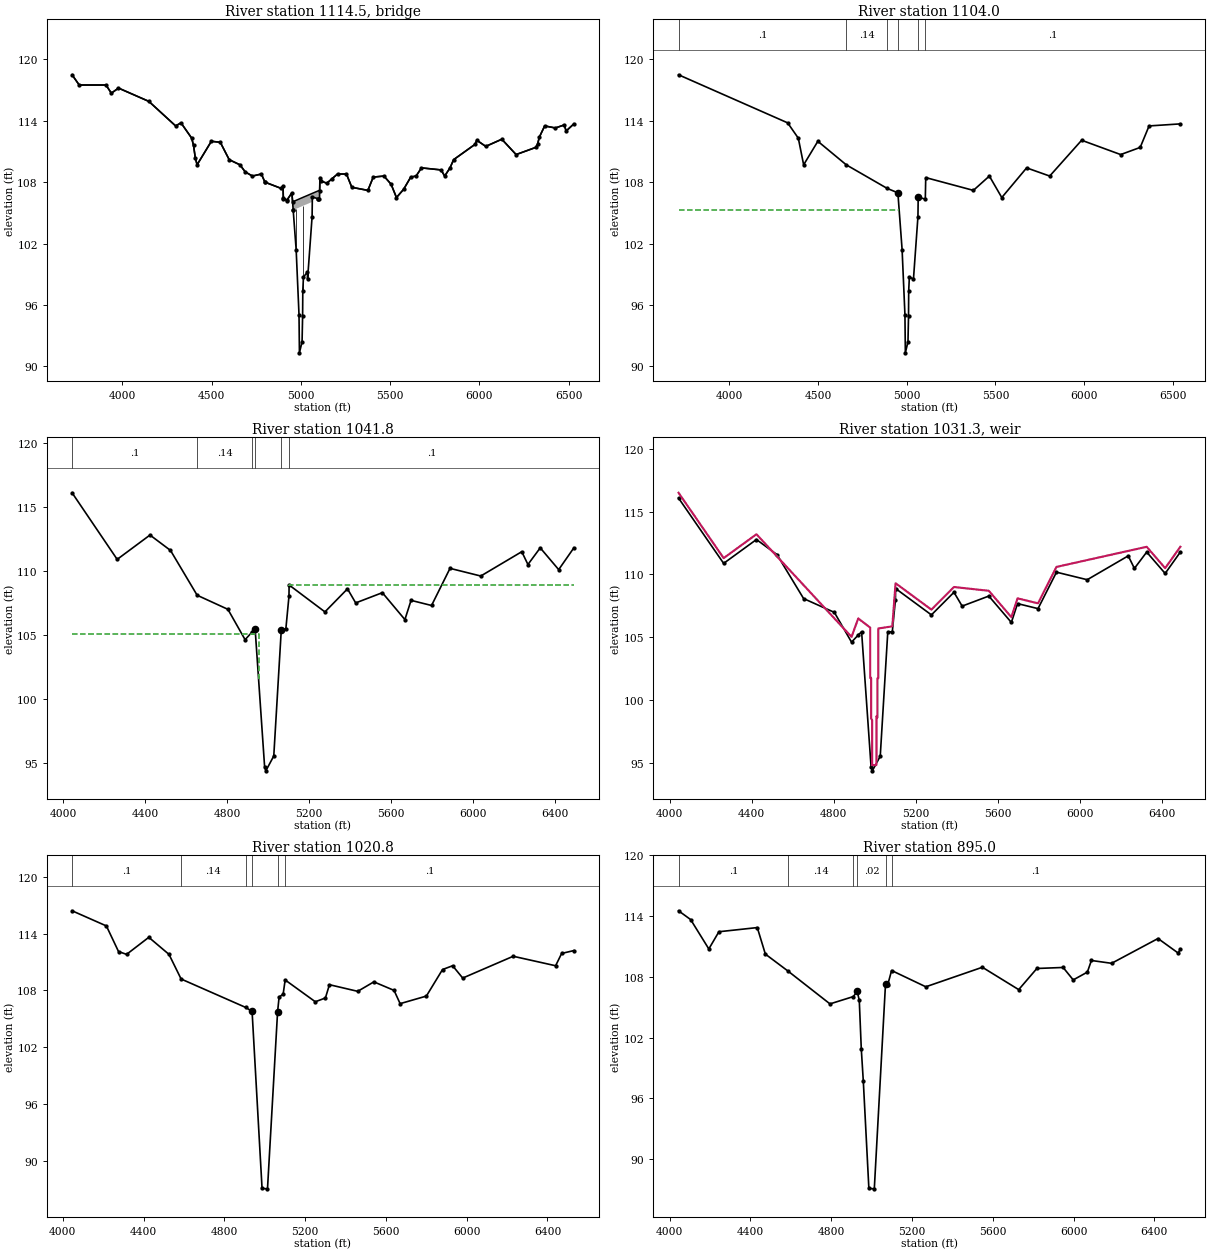
Type RM Length L Ch R = 3 ,1114.5  ,,,
BEGIN DESCRIPTION:
PL1_K131-02-00-S1
END DESCRIPTION:
Bridge Culvert--1,0,-1,-1, 0
Deck Dist Width WeirC Skew NumUp NumDn MinLoCord MaxHiCord MaxSubmerge Is_Ogee
10,1,2.6,0, 79, 79, , , .95, 0, ,,,
  3719.1  3759.1  3909.1  3939.1  3979.1  4149.1  4299.1  4329.1  4389.1  4399.1
  4409.1  4419.1  4499.1  4549.1  4599.1  4659.1  4689.1  4729.1  4779.1  4799.1
  4799.8  4889.1  4900.5 4902.21 4903.01 4920.21 4920.61 4950.11 4953.81 4957.22
 4957.31 4973.91 4989.91 4992.21 5007.01 5010.11 5011.11 5014.81 5036.71 5037.91
 5063.21 5064.61  5095.4 5095.51 5104.61 5105.51 5107.11  5115.6  5145.6  5173.5
  5205.6  5255.6  5285.6  5375.6  5405.6  5465.6  5505.6  5535.6  5575.6  5615.6
  5645.6  5675.6  5785.6  5805.6  5835.6  5855.6  5975.6  5985.6  6035.6  6125.6
  6205.6  6315.6  6325.6  6335.6  6365.6  6425.6  6475.6  6485.6    6529
   118.5   117.5   117.5   116.7   117.2   115.9   113.5   113.8   112.3   111.6
   110.4   109.7     112   111.9   110.2   109.7     109   108.6   108.8     108
     108   107.4   107.6  106.38  106.48  106.23   106.2  106.96  106.11  106.11
  106.11  106.23  106.35  106.37  106.48   106.5  106.51  106.54   106.7  106.71
   106.9  106.91  107.14  107.14  107.21  107.22  108.45   108.1   107.9  108.32
   108.8   108.8   107.5   107.2   108.5   108.6   107.8   106.5   107.3   108.5
   108.6   109.4   109.2   108.6   109.4   110.2   111.7   112.1   111.5   112.2
   110.7   111.4   111.7   112.4   113.5   113.3   113.6     113   113.7
                                                                                
                                                                                
                                                                   106.1   105.3
  105.28   105.4  105.52  105.54  105.65  105.67  105.68  105.71  105.87  105.88
  106.07  106.09
                                                                                
                                                                                
                                                                        
  3719.1  3759.1  3909.1  3939.1  3979.1  4149.1  4299.1  4329.1  4389.1  4399.1
  4409.1  4419.1  4499.1  4549.1  4599.1  4659.1  4689.1  4729.1  4779.1  4799.1
  4799.8  4889.1  4900.5 4902.21 4903.01 4920.21 4920.61 4950.11 4953.81 4957.22
 4957.31 4973.91 4989.91 4992.21 5007.01 5010.11 5011.11 5014.81 5036.71 5037.91
 5063.21 5064.61  5095.4 5095.51 5104.61 5105.51 5107.11  5115.6  5145.6  5173.5
  5205.6  5255.6  5285.6  5375.6  5405.6  5465.6  5505.6  5535.6  5575.6  5615.6
  5645.6  5675.6  5785.6  5805.6  5835.6  5855.6  5975.6  5985.6  6035.6  6125.6
  6205.6  6315.6  6325.6  6335.6  6365.6  6425.6  6475.6  6485.6    6529
   118.5   117.5   117.5   116.7   117.2   115.9   113.5   113.8   112.3   111.6
   110.4   109.7     112   111.9   110.2   109.7     109   108.6   108.8     108
     108   107.4   107.6  106.38  106.48  106.23   106.2  106.96  106.11  106.11
  106.11  106.23  106.35  106.37  106.48   106.5  106.51  106.54   106.7  106.71
   106.9  106.91  107.14  107.14  107.21  107.22  108.45   108.1   107.9  108.32
   108.8   108.8   107.5   107.2   108.5   108.6   107.8   106.5   107.3   108.5
   108.6   109.4   109.2   108.6   109.4   110.2   111.7   112.1   111.5   112.2
   110.7   111.4   111.7   112.4   113.5   113.3   113.6     113   113.7
                                                                                
                                                                                
                                                                   106.1   105.3
  105.28   105.4  105.52  105.54  105.65  105.67  105.68  105.71  105.87  105.88
  106.07  106.09
                                                                                
                                                                                
                                                                        
Pier Skew, UpSta & Num, DnSta & Num=  ,4973.9, 2 ,4973.9, 2 , 0 , 0 , 0 ,,
     1.2     1.2
  100.17   106.4
     1.2     1.2
  100.17   106.4
Pier Skew, UpSta & Num, DnSta & Num=  ,5011.1, 2 ,5011.1, 2 , 0 , 0 , 0 ,,
     1.2     1.2
   94.93  106.68
     1.2     1.2
   94.93  106.68
Pier Skew, UpSta & Num, DnSta & Num=  ,5063.2, 2 ,5063.2, 2 , 0 , 0 , 0 ,,
     1.2     1.2
   103.5  107.28
     1.2     1.2
   103.5  107.28
BR Coef= 1 , 1 , 1 ,1.25, 0 ,,,.8,0,2,0,
WSPro=,,,, 1 ,,,, 0 ,,,, 0 ,,,,-1 ,-1 ,-1 , 0 , 0 , 0 , 0 , 0
BR U #Sta/Elev= 79
  3719.1   118.5  3759.1   117.5  3909.1   117.5  3939.1   116.7  3979.1   117.2
  4149.1   115.9  4299.1   113.5  4329.1   113.8  4389.1   112.3  4399.1   111.6
  4409.1   110.4  4419.1   109.7  4499.1     112  4549.1   111.9  4599.1   110.2
  4659.1   109.7  4689.1     109  4729.1   108.6  4779.1   108.8  4799.1     108
  4799.8     108  4889.1   107.4  4900.5   107.6 4902.21  106.38 4903.01  106.48
 4920.21  106.23 4920.61   106.2 4950.11  106.96 4953.81   106.1 4957.22   105.3
 4957.31  105.28 4973.91  101.41 4989.91   95.04 4992.21   91.32 5007.01   92.39
 5010.11   94.96 5011.11   97.39 5014.81   98.73 5036.71   99.21 5037.91   98.53
 5063.21  104.64 5064.61  106.55  5095.4  106.39 5095.51  106.39 5104.61  106.34
 5105.51   107.1 5107.11  108.45  5115.6   108.1  5145.6   107.9  5173.5  108.32
  5205.6   108.8  5255.6   108.8  5285.6   107.5  5375.6   107.2  5405.6   108.5
  5465.6   108.6  5505.6   107.8  5535.6   106.5  5575.6   107.3  5615.6   108.5
  5645.6   108.6  5675.6   109.4  5785.6   109.2  5805.6   108.6  5835.6   109.4
  5855.6   110.2  5975.6   111.7  5985.6   112.1  6035.6   111.5  6125.6   112.2
  6205.6   110.7  6315.6   111.4  6325.6   111.7  6335.6   112.4  6365.6   113.5
  6425.6   113.3  6475.6   113.6  6485.6     113    6529   113.7
BR U #Mann= 6
  3719.1      .1  4659.1     .14  4889.1     .06 4950.11     .04 5064.61     .06
 5104.61      .1
BR U Banks=4950.11,5064.61
BR D #Sta/Elev= 79
  3714.1   118.5  3759.1   117.5  3909.1   117.5  3939.1   116.7  3979.1   117.2
  4149.1   115.9  4299.1   113.5  4329.1   113.8  4389.1   112.3  4399.1   111.6
  4409.1   110.4  4419.1   109.7  4499.1     112  4549.1   111.9  4599.1   110.2
  4659.1   109.7  4689.1     109  4729.1   108.6  4779.1   108.8  4799.1     108
  4799.8     108  4889.1   107.4  4900.5   107.6 4902.21  106.38 4903.01  106.48
 4920.21  106.23 4920.61   106.2 4950.11  106.96 4953.81   106.1 4957.22   105.3
 4957.31  105.28 4973.91  101.41 4989.91   95.04 4992.21   91.32 5007.01   92.39
 5010.11   94.96 5011.11   97.39 5014.81   98.73 5036.71   99.21 5037.91   98.53
 5063.21  104.64 5064.61  106.55  5095.4  106.39 5095.51  106.39 5104.61  106.34
 5105.51   107.1 5107.11  108.45  5115.6   108.1  5145.6   107.9  5173.5  108.32
  5205.6   108.8  5255.6   108.8  5285.6   107.5  5375.6   107.2  5405.6   108.5
  5465.6   108.6  5505.6   107.8  5535.6   106.5  5575.6   107.3  5615.6   108.5
  5645.6   108.6  5675.6   109.4  5785.6   109.2  5805.6   108.6  5835.6   109.4
  5855.6   110.2  5975.6   111.7  5985.6   112.1  6035.6   111.5  6125.6   112.2
  6205.6   110.7  6315.6   111.4  6325.6   111.7  6335.6   112.4  6365.6   113.5
  6425.6   113.3  6475.6   113.6  6485.6     113  6541.7   113.7
BR D #Mann= 6
  3714.1      .1  4659.1     .14  4889.1     .06 4950.11     .04 5064.61     .06
 5104.61      .1
BR D Banks=4950.11,5064.61
BC Design=,, 0 ,, 0 ,,,,,,

Type RM Length L Ch R = 1 ,1104.0  ,93.9,62.2,43.9
BEGIN DESCRIPTION:
Downstream Section of Bridge/Culvert/Weir
END DESCRIPTION:
XS GIS Cut Line= 4
      3072237.19     13936584.34      3072927.74     13935625.38
      3073047.54     13935448.21      3072750.86     13934047.39
#Sta/Elev= 30
  3714.1   118.5  4329.1   113.8  4389.1   112.3  4419.1   109.7  4499.1     112
  4659.1   109.7  4889.1   107.4 4950.11  106.96 4973.91  101.41 4989.91   95.04
 4992.21   91.32 5007.01   92.39 5010.11   94.96 5011.11   97.39 5014.81   98.73
 5037.91   98.53 5063.21  104.64 5064.61  106.55 5104.61  106.34 5107.11  108.45
  5375.6   107.2  5465.6   108.6  5535.6   106.5  5675.6   109.4  5805.6   108.6
  5985.6   112.1  6205.6   110.7  6315.6   111.4  6365.6   113.5  6541.7   113.7
#Mann= 6 ,-1 , 0
  3714.1      .1       0  4659.1     .14       0  4889.1     .06       0
 4950.11     .04       0 5064.61     .06       0 5104.61      .1       0
#XS Ineff= 2 , 0
       0 4957.31   105.3 5064.27       0  106.08
Permanent Ineff=
       F       F
Bank Sta=4950.11,5064.61
XS Rating Curve= 0
Exp/Cntr=.5,.3

Type RM Length L Ch R = 1 ,1041.8  ,20,21,22
BEGIN DESCRIPTION:
Upstream Section of Bridge/Culvert/Weir
END DESCRIPTION:
XS GIS Cut Line= 5
      3072666.63     13936437.35      3073050.12     13935579.17
       3073062.6     13935542.76      3073094.09     13935442.86
      3072884.72     13934095.06
#Sta/Elev= 30
    4044  116.08    4264  110.88    4424  112.78    4524  111.58    4654  108.08
    4804  106.98  4887.8  104.61  4920.3  105.18  4936.8  105.44    4983   94.69
    4989   94.37  5027.7   95.53  5064.4   105.4  5086.6  105.45  5101.8     108
  5102.5  108.88  5277.2  106.78  5387.2  108.58  5427.2  107.48  5557.2  108.28
  5667.2  106.18  5697.2  107.68  5797.2  107.28  5887.2  110.18  6037.2  109.58
  6237.2  111.48  6267.2  110.48  6327.2  111.78  6417.2  110.08  6491.2  111.78
#Mann= 6 ,-1 , 0
    4044      .1       0    4654     .14       0  4920.3     .06       0
  4936.8     .02       0  5064.4     .06       0  5101.8      .1       0
#XS Ineff= 2 , 0
       0 4953.81  105.03 5102.43       0   108.9
Permanent Ineff=
       F       F
Bank Sta=4936.8,5064.4
XS Rating Curve= 0
Exp/Cntr=.7,.5

Type RM Length L Ch R = 5 ,1031.3  ,,,
BEGIN DESCRIPTION:
SHEET PILING STRUC. 2050' DS SIR WILLIAM DR.
Structure ID: K131-02-00-S1B
END DESCRIPTION:
IW Pilot Flow=0
#Inline Weir SE= 30
    4044   116.5    4264   111.3    4424   113.2  4887.8  105.03  4920.3   106.5
  4978.7  105.77  4978.9  101.76  4983.1  101.77  4983.3   98.53    4988   98.42
  4988.2   94.84    4989   94.81  5009.2   94.83  5009.4   98.73  5013.7    98.6
  5013.8  101.73  5018.1  101.74  5018.3   105.7  5086.6  105.87  5102.5   109.3
  5277.2   107.2  5387.2     109  5557.2   108.7  5667.2   106.6  5697.2   108.1
  5797.2   107.7  5887.2   110.6  6327.2   112.2  6417.2   110.5  6491.2   112.2
IW Dist,WD,Coef,Skew,MaxSub,Min_El,Is_Ogee,SpillHt,DesHd
10,1,3,0,.95,, 0 ,,,0,0,

Type RM Length L Ch R = 1 ,1020.8  ,124,125.8,127
BEGIN DESCRIPTION:
Cross Section FIELD_DS
Located At: SHEET PILING STRUC. 2050' DS SIR WILLIAM DR.
END DESCRIPTION:
XS GIS Cut Line= 5
      3072722.68     13936457.64       3073069.7     13935590.79
      3073083.56     13935551.57      3073123.96     13935450.07
      3072901.51     13934067.38
#Sta/Elev= 30
  4045.7   116.4  4215.7   114.8  4275.7   112.1  4315.7   111.8  4425.7   113.6
  4525.7   111.8  4585.7   109.2  4905.7   106.2  4937.2  105.78  4986.6    87.1
  5013.5   87.06  5063.4  105.72    5071   107.3    5091   107.6    5101   109.1
  5250.3   106.8  5300.3   107.2  5320.3   108.6  5460.3   107.9  5540.3   108.9
  5640.3     108  5670.3   106.6  5800.3   107.4  5880.3   110.2  5930.3   110.6
  5980.3   109.3  6230.3   111.6  6440.3   110.6  6470.3   111.9  6530.7   112.2
#Mann= 6 ,-1 , 0
  4045.7      .1       0  4585.7     .14       0  4905.7     .06       0
  4937.2     .02       0  5063.4     .06       0    5101      .1       0
Bank Sta=4937.2,5063.4
XS Rating Curve= 0
Exp/Cntr=.7,.5

Type RM Length L Ch R = 1 ,895.0   ,0,0,0
BEGIN DESCRIPTION:
DAM-S1B_DS FIELD - XS 1
Located At: SHEET PILING STRUC. 2050' DS SIR WILLIAM DR.
END DESCRIPTION:
XS GIS Cut Line= 4
        3072834.      13936498.6       3073141.3     13935732.65
       3073235.7     13935491.04      3073013.25     13934108.35
#Sta/Elev= 30
    4044  114.53    4104  113.66    4194  110.76    4244  112.46    4434  112.87
    4474  110.25    4587  108.56    4794  105.33  4909.1  106.05  4929.1  106.56
  4939.1  105.67  4949.1  100.86  4959.1   97.68  4986.6    87.1  5013.5   87.06
  5069.1  107.34  5079.1  107.15  5099.1  108.63  5268.6  107.02  5548.6  108.95
  5728.6  106.74  5818.6  108.83  5948.6  108.93  5998.6   107.7  6068.6  108.47
  6088.6  109.62  6188.6  109.34  6418.6  111.79  6518.6  110.35    6529  110.76
#Mann= 6 ,-1 , 0
    4044      .1       0    4587     .14       0  4909.1     .06       0
  4929.1     .02       0  5069.1     .06       0  5099.1      .1       0
Bank Sta=4929.1,5069.1
XS Rating Curve= 0
Exp/Cntr=.3,.1

Chan Stop Cuts=-1